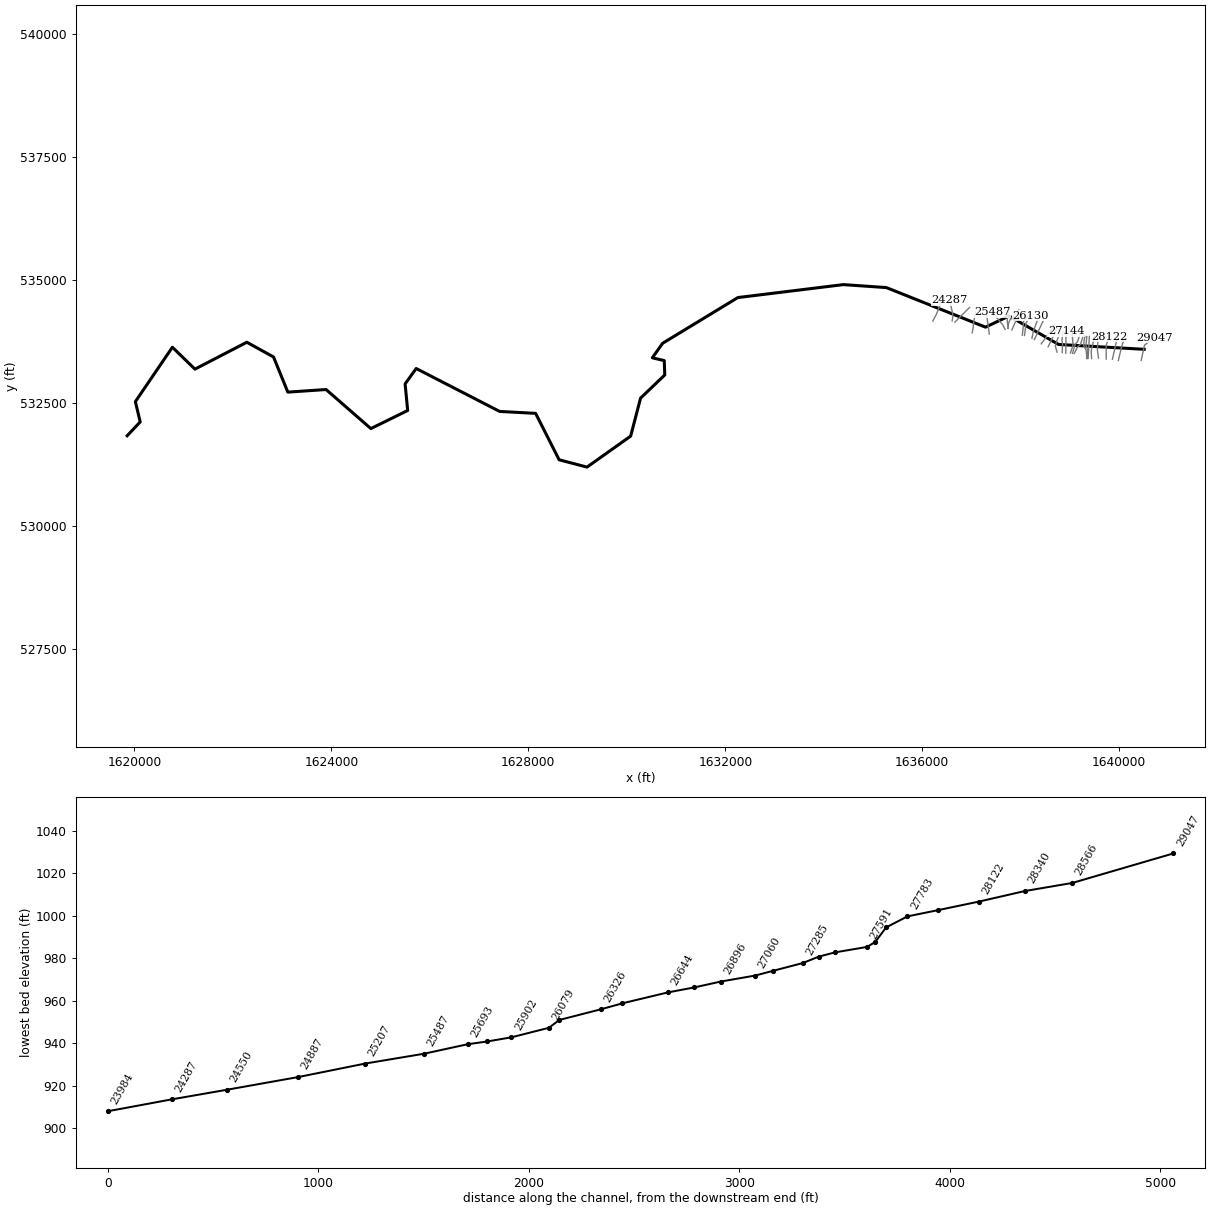
--- LtlGraveCk.prj (project) ---

Proj Title=LtlGraveCk
Current Plan=p01
Default Exp/Contr=0,0
English Units
Geom File=g01
Flow File=f01
Plan File=p01
BEGIN DESCRIPTION:
---------- MODELED AS PART OF WVEM CTP PROGRAM, 2025----------
Stream Name: Little Grave Creek
Flood Zone: AFH
Marshall County, WV
HEC-RAS Version: RAS 6.6
Vertical Datum: NAVD88
Projection: NAD 1983 StatePlane West Virginia N FIPS 4701 (US Feet)
Terrain: 1-meter West Virginia FEMA R3 South Central (collected 2018-2019)
Land Use: 2024 NLCD
Hydrologic Method:
Duda et al., "Estimation of magnitude and frequency of floods for rural, unregulated streams in and near Virginia and West Virginia." September 8, 2025.
Additional Model Notes:
None
END DESCRIPTION:
DSS Export Rating Curves= 0
DSS Export Rating Curve Sorted= 0
DSS Export Volume Flow Curves= 0
DXF OffsetX= 0
DXF OffsetY= 0
DXF ScaleX= 0
DXF ScaleY= 0

--- LtlGraveCk.p01 (plan) ---

Plan Title=Floodplain
Program Version=6.60
Short Identifier=Floodplain
Geom File=g01
Flow File=f01
Subcritical Flow
K Sum by GR= 0
Std Step Tol= 0.01
Critical Tol= 0.01
Num of Std Step Trials= 20
Max Error Tol= 0.3
Flow Tol Ratio= 0.001
Split Flow NTrial= 30
Split Flow Tol= 0.02
Split Flow Ratio= 0.02
Log Output Level= 0
Friction Slope Method= 1
Unsteady Friction Slope Method= 2
Unsteady Bridges Friction Slope Method= 1
Parabolic Critical Depth
Global Vel Dist= 0 , 0 , 0
Global Log Level= 0
CheckData=False
Encroach Param=-1 ,0,0, 0
Flow Ratio Tolerance=0.1
Flow Ratio Min Ratio=0.5
Flow Ratio Max Ratio=4
Flow Ratio Max Iterations= 10
Mapping Interval=1HOUR
Computation Time Step Use Courant=        0
Computation Time Step Use Time Series=    0
Computation Time Step Count To Double=0
Computation Time Step Max Doubling=0
Computation Time Step Max Halving=0
Computation Time Step Residence Courant=0
Run HTab= 0
Run UNet= 0
Run Sediment= 0
Run PostProcess= 0
Run WQNet= 0
Run RASMapper=-1
UNET Theta= 0
UNET Theta Warmup= 0
UNET ZTol= 0
UNET ZSATol= 0
UNET MxIter= 0
UNET Max Iter WO Improvement= 0
UNET MaxInSteps= 0
UNET DtIC= 0
UNET DtMin= 0
UNET MaxCRTS= 0
UNET WFStab= 0
UNET SFStab= 0
UNET WFX= 1
UNET SFX= 1
UNET Gravity=32.17405
UNET 1D Methodology=Finite Difference
UNET DSS MLevel= 1
UNET Pardiso=0
UNET DZMax Abort= 0
UNET Use Existing IB Tables= 0
UNET Froude Reduction=False
UNET Froude Limit= 0
UNET Froude Power= 0
UNET D1 Cores= 0
UNET WindReference=Eulerian
UNET WindDragFormulation=Hsu (1988)
UNET D2 Coriolis=0
UNET D2 Cores= 0
UNET D2 Theta= 1
UNET D2 Theta Warmup= 1
UNET D2 Z Tol= 0.01
UNET D2 Volume Tol= 0.01
UNET D2 Max Iterations= 20
UNET D2 Advanced Convergence=0
UNET D2 WS Max Tol=0.15
UNET D2 WS RMS Tol=0.002
UNET D2 WS Stall Tol=1
UNET D2 Equation= 0
UNET D2 RampUpFraction=0.1
UNET D2 TimeSlices= 1
UNET D2 Turbulence Formulation=Non-Conservative (original)
UNET D2 Eddy Viscosity=0.3
UNET D2 Transverse Eddy Viscosity=0.1
UNET D2 Smagorinsky Mixing=0
UNET D2 BCVolumeCheck=0
UNET D2 Cores=0
UNET D2 SolverType=PARDISO (Direct)
UNET D2 Minimum Iterations= 3
UNET D2 Maximum Iterations= 30
UNET D2 Restart Number= 10
UNET D2 Relaxation Coeff=1.3
UNET D2 SOR Precondition Iterations= 10
UNET D2 ILUT Maximum Fill= 8
UNET D2 ILUT Tolerance=1E-08
UNET D2 Convergence Tolerance=0.00001
PS Theta= 1
PS WS Tol= 0.01
PS Volume Tol= 0.01
PS Max Iterations= 20
PS Equation= 0
PS Advance Time Step=-1
PS Target Courant=0.9
PS Time Slices= 1
PS Iterate With 2D=0
PS Project Initial WSE from DS=-1
PS Ramp Up Initial WSE from US=-1
PS Cores=0
UNET D1D2 MaxIter= 0
UNET D1D2 ZTol=0.01
UNET D1D2 QTol=0.1
UNET D1D2 MinQTol=1
Write IC File= 0
Write IC File at Fixed DateTime=0
Write IC File at Sim End=0
Echo Input=False
Echo Parameters=False
Echo Output=False
Write Detailed= 0
HDF Write Warmup=0
HDF Write Time Slices=0
HDF Flush=0
HDF Compression= 1
HDF Chunk Size= 1
HDF Spatial Parts= 1
HDF Use Max Rows=0
HDF Fixed Rows= 1
Calibration Method= 0
Calibration Iterations= 20
Calibration Max Change=0.05
Calibration Tolerance=0.2
Calibration Maximum=1.5
Calibration Minimum=0.5
Calibration Optimization Method= 1
WQ AD Non Conservative
WQ ULTIMATE=-1
WQ Max Comp Step=1HOUR
WQ Output Interval=15MIN
WQ Output Selected Increments= 0
WQ Create Restart=0
WQ Fixed Restart=0
WQ System Summary=0
WQ Write To DSS=0
Sorting and Armoring Iterations= 10
XS Update Threshold= 0.02
Bed Roughness Predictor= 0
Processes Affected by Predictor=Sediment Only
Hydraulics Update Threshold= 0.02
Energy Slope Method= 1
Volume Change Method= 1
Sediment Retention Method= 0
Sediment TS Multiplier= 1
Warm Up Method= 0
XS Weighting Method= 0
Number of US Weighted Cross Sections= 1
Number of DS Weighted Cross Sections= 1
Upstream XS Weight=0
Main XS Weight=1
Downstream XS Weight=0
Number of DS XS's Weighted with US Boundary= 1
Upstream Boundary Weight= 1
Weight of XSs Associated with US Boundary= 0
Number of US XS's Weighted with DS Boundary= 1
Downstream Boundary Weight= 0.5
Weight of XSs Associated with DS Boundary= 0.5
Percentile Method= 0
Sediment Output Level= 3
Mass or Volume Output= 0
Output Increment Type= 1
Profile and TS Output Increment= 1
Transport Output Increment 1
XS Output Flag= 0
XS Output Increment= 10
Read HDF5 Sediment Hotstart= 0
Sediment Hotstart Type= 0
Write Gradation File= 0
Read Gradation Hotstart= 0
Write HDF5 File= 1
Write Binary Output= 1
Write DSS Sediment File= 0
DSS Sediment Output Type= 1
SV Curve= 0
Specific Gage Flag= 0
Subcell Erosion Methods= 0
Subcell Deposition Methods= 0
Advection Scheme= 1
Matrix Solver= 0
Implicit Weighting Factor= 1
Maximum Outer Loop Convergence Iterations= 5
Convergence Maximum Absolute= 0.001
Convergence RMSE= 0.0001
Grain Fractions Max Abs Error= 0.001
Max Subgrid Regions= 1
Max Subgrid Length Scale= 3.402823E+38
Initial Layer Thickness= 3
Min Layer Thickness= 0.1
Max Layer Thickness= 6
Number of Layers= 5

--- LtlGraveCk.f01 (steady flow) ---

Flow Title=Flow
Program Version=6.60
Number of Profiles= 1
Profile Names=P100yr
River Rch & RM=LtlGraveCk,Main            ,29047
     667
River Rch & RM=LtlGraveCk,Main            ,28566
     746
River Rch & RM=LtlGraveCk,Main            ,26079
     996
River Rch & RM=LtlGraveCk,Main            ,22929
    1150
River Rch & RM=LtlGraveCk,Main            ,19671
    2220
River Rch & RM=LtlGraveCk,Main            ,15084
    2470
River Rch & RM=LtlGraveCk,Main            ,9287
    2760
Boundary for River Rch & Prof#=LtlGraveCk,Main            , 1
Up Type= 0
Dn Type= 1
Dn Known WS=685.5
DSS Import GetInterval= 0
DSS Import GetPeak= 0
DSS Import FillOption= 0

--- LtlGraveCk.g01 (geometry) ---

Geom Title=Geometry
Program Version=6.60

River Reach=LtlGraveCk      ,Main
Reach XY= 30
     1640507.317      533598.969     1638767.665      533697.548
     1637761.898      534276.318     1637284.162      534049.238
     1635270.841       534853.21      1634398.01      534913.764
     1632255.174      534650.609     1630727.004      533721.664
     1630517.533      533426.427     1630759.752      533369.965
      1630770.42      533077.947     1630279.209      532607.115
     1630077.691      531834.984      1629191.41      531205.472
     1628624.808      531354.205     1628147.952      532297.432
     1627416.869      532336.777     1625722.493      533209.066
     1625497.347      532896.547     1625549.482      532355.837
     1624802.113      531988.185     1623892.343      532781.683
     1623115.666      532729.241     1622825.287      533443.054
     1622282.747      533742.835      1621229.22      533195.977
     1620771.383      533641.236     1620019.536      532535.991
     1620117.702       532123.551619852.36508273531841.995124102

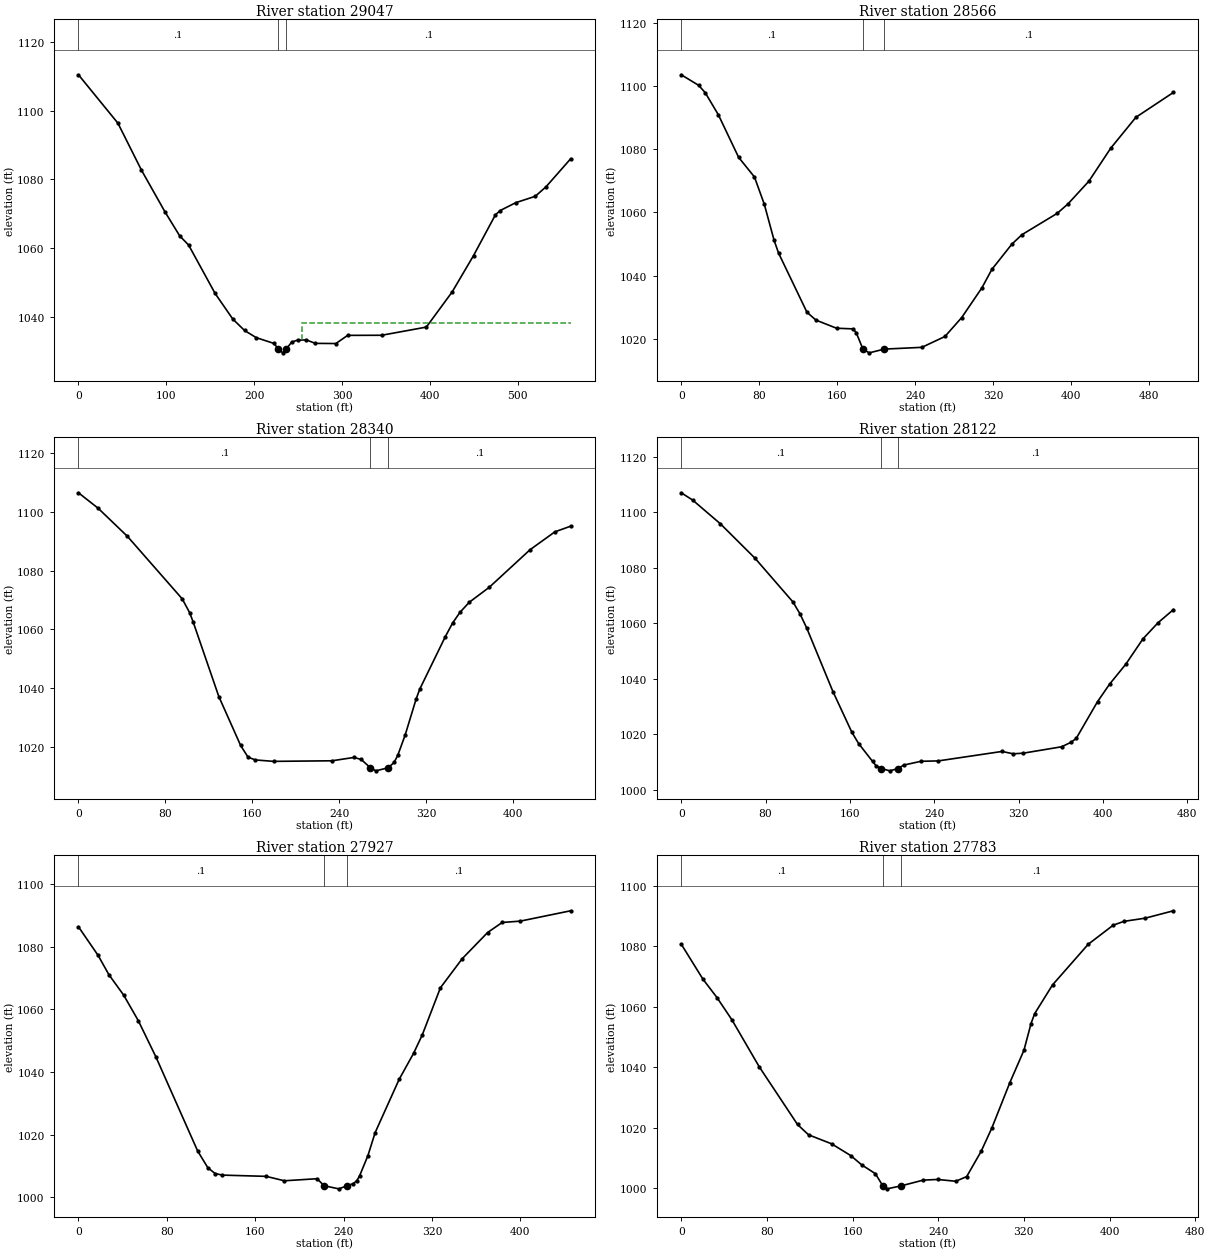
Type RM Length L Ch R = 1 ,29047   ,481.1,480.9,475.9
XS GIS Cut Line= 3
1640446.06259282533374.6706889011640511.60574521533681.762791121
1640707.16252252533831.612183974
#Sta/Elev= 30
       0 1110.46    44.9 1096.37    71.7 1082.69    98.5 1070.53   115.3 1063.52
   125.4 1060.87   155.6 1046.75   175.7 1039.31   189.1 1035.97   202.4 1033.89
   222.7 1032.19  227.261030.651   232.7 1029.46  236.731030.649   242.8 1032.59
   249.4 1033.16   259.6 1033.22   269.6 1032.22   293.1 1032.17   306.5 1034.55
   345.2 1034.58   396.1 1036.96   425.5 1047.21   449.8 1057.78   474.6  1069.6
     480 1070.89     498 1073.21   520.1 1075.06   532.5 1077.87   560.4 1085.99
#Mann= 3, -1 ,  0
       0     0.1       0  227.26   0.045       0  236.73     0.1       0
#XS Ineff= 2 , 0
                          254.73         1038.16
Permanent Ineff=
       F       F
Bank Sta=227.26,236.73
XS Rating Curve= 0 ,0
Exp/Cntr=0.3,0.1

Type RM Length L Ch R = 1 ,28566   ,223,225.8,211.9
XS GIS Cut Line= 3
 1639982.1247593533371.6241318541640042.01212292533629.566979272
1640113.69012303 533858.84044059
#Sta/Elev= 30
       0 1103.51    17.9 1100.17    24.6 1097.85    38.1 1090.85    58.9 1077.38
    75.1 1071.19    85.2 1062.57    95.3 1051.11    99.9 1047.07     129 1028.37
   138.2  1025.9   159.3 1023.33   176.2 1023.12   179.5 1021.96  186.43 1016.71
   192.9 1015.54  208.27 1016.72   246.9 1017.28   270.6 1020.72   287.8 1026.72
   308.5 1036.11   318.7 1041.94   339.3 1049.95   349.6 1052.93   385.7 1059.66
   396.7 1062.62   418.3 1069.86   440.7  1080.3   466.5 1090.06     505 1097.93
#Mann= 3, -1 ,  0
       0     0.1       0  186.43   0.045       0  208.27     0.1       0
Bank Sta=186.43,208.27
XS Rating Curve= 0 ,0
Exp/Cntr(USF)=0,0
Exp/Cntr=0.3,0.1

Type RM Length L Ch R = 1 ,28340   ,216.2,218.6,219.4
XS GIS Cut Line= 2
1639861.03182568533397.5499722511639960.88860995533839.488612201
#Sta/Elev= 30
       0 1106.57      18 1101.33    45.1  1091.7    95.5 1070.39   102.3 1065.72
   105.6 1062.49   129.2 1037.08   149.3 1020.38   156.1  1016.4   162.8 1015.45
   179.6 1014.96   233.4 1015.16   253.6  1016.3   260.3 1015.61  268.711012.788
   273.8 1011.73  285.15 1012.79   290.6  1014.6     294 1017.07   300.7 1023.89
   310.8 1036.18   314.2 1039.61   337.7 1057.49   344.5 1062.19   351.2 1065.78
   359.7 1069.21   378.1 1074.31   415.8 1087.17   438.6 1093.25   453.1 1095.18
#Mann= 3, -1 ,  0
       0     0.1       0  268.71   0.045       0  285.15     0.1       0
Bank Sta=268.71,285.15
XS Rating Curve= 0 ,0
Exp/Cntr(USF)=0,0
Exp/Cntr=0.3,0.1

Type RM Length L Ch R = 1 ,28122   ,191.3,195,192.1
XS GIS Cut Line= 3
1639735.32731808533401.1457082391639734.76446161533683.413909128
1639801.43658039533855.614328824
#Sta/Elev= 30
       0 1106.98    10.8 1104.36    37.1 1095.81    69.9 1083.42     106 1067.61
   112.6 1063.37   119.1 1058.17   143.9 1035.32   161.8 1020.69   168.3 1016.57
   181.5 1010.14   184.7 1008.65  189.791007.589   197.9 1006.75  205.651007.587
     211 1008.82   227.4 1010.19   243.8 1010.33   304.3 1013.74   314.9 1012.89
   324.5 1013.12   360.9 1015.43   369.9 1017.08   374.7 1018.45   394.9 1031.69
   406.3 1037.98   421.6 1045.13     438 1054.33   452.3 1060.13   466.9 1064.87
#Mann= 3, -1 ,  0
       0     0.1       0  189.79   0.045       0  205.65     0.1       0
Bank Sta=189.79,205.65
XS Rating Curve= 0 ,0
Exp/Cntr(USF)=0,0
Exp/Cntr=0.3,0.1

Type RM Length L Ch R = 1 ,27927   ,138.8,143.3,137.8
XS GIS Cut Line= 3
 1639578.6351065533423.9986164771639556.65088926533581.720807823
 1639573.2237242533867.607118764
#Sta/Elev= 30
       0 1086.31    17.7 1077.23    27.6 1071.01    40.9 1064.53    54.1 1056.41
    70.1 1044.81   107.9 1014.79   117.1 1009.46   123.7  1007.6   130.3 1007.09
     170 1006.69   186.4 1005.28     216 1005.94  222.431003.693   235.7 1002.71
  243.251003.696   248.9 1004.39   252.1 1005.35   254.6 1006.92     262 1013.26
   268.6 1020.65   290.3 1037.62   303.4 1045.95   311.3 1051.85   327.7 1066.86
   347.4 1076.12   370.4 1084.48   383.6 1087.69     400 1088.12   445.6 1091.42
#Mann= 3, -1 ,  0
       0     0.1       0  222.43   0.045       0  243.25     0.1       0
Bank Sta=222.43,243.25
XS Rating Curve= 0 ,0
Exp/Cntr(USF)=0,0
Exp/Cntr=0.3,0.1

Type RM Length L Ch R = 1 ,27783   ,94.9,101.5,97.9
XS GIS Cut Line= 4
1639438.68162608533411.4637855661639429.42506947533566.180517527
1639460.20679344533690.3359197171639491.13544689533864.373876989
#Sta/Elev= 30
       0 1080.65    20.3 1069.07    33.4    1063    47.3 1055.67    72.8 1040.16
   108.6 1021.07   118.9 1017.66   140.4 1014.69   158.4 1010.78   168.5 1007.74
   181.3 1004.83  188.37 1000.75   192.2  999.81  204.891000.753     226 1002.69
   239.5 1002.91   256.4 1002.31   266.6 1003.86   280.1  1012.2   290.1 1019.91
   306.9 1034.89   320.1 1045.61   326.7 1054.43   330.1  1057.7   346.8  1067.2
   380.1 1080.61   403.4 1086.91   413.4 1088.18   433.4 1089.24   459.7 1091.68
#Mann= 3, -1 ,  0
       0     0.1       0  188.37   0.045       0  204.89     0.1       0
Bank Sta=188.37,204.89
XS Rating Curve= 0 ,0
Exp/Cntr(USF)=0,0
Exp/Cntr=0.3,0.1

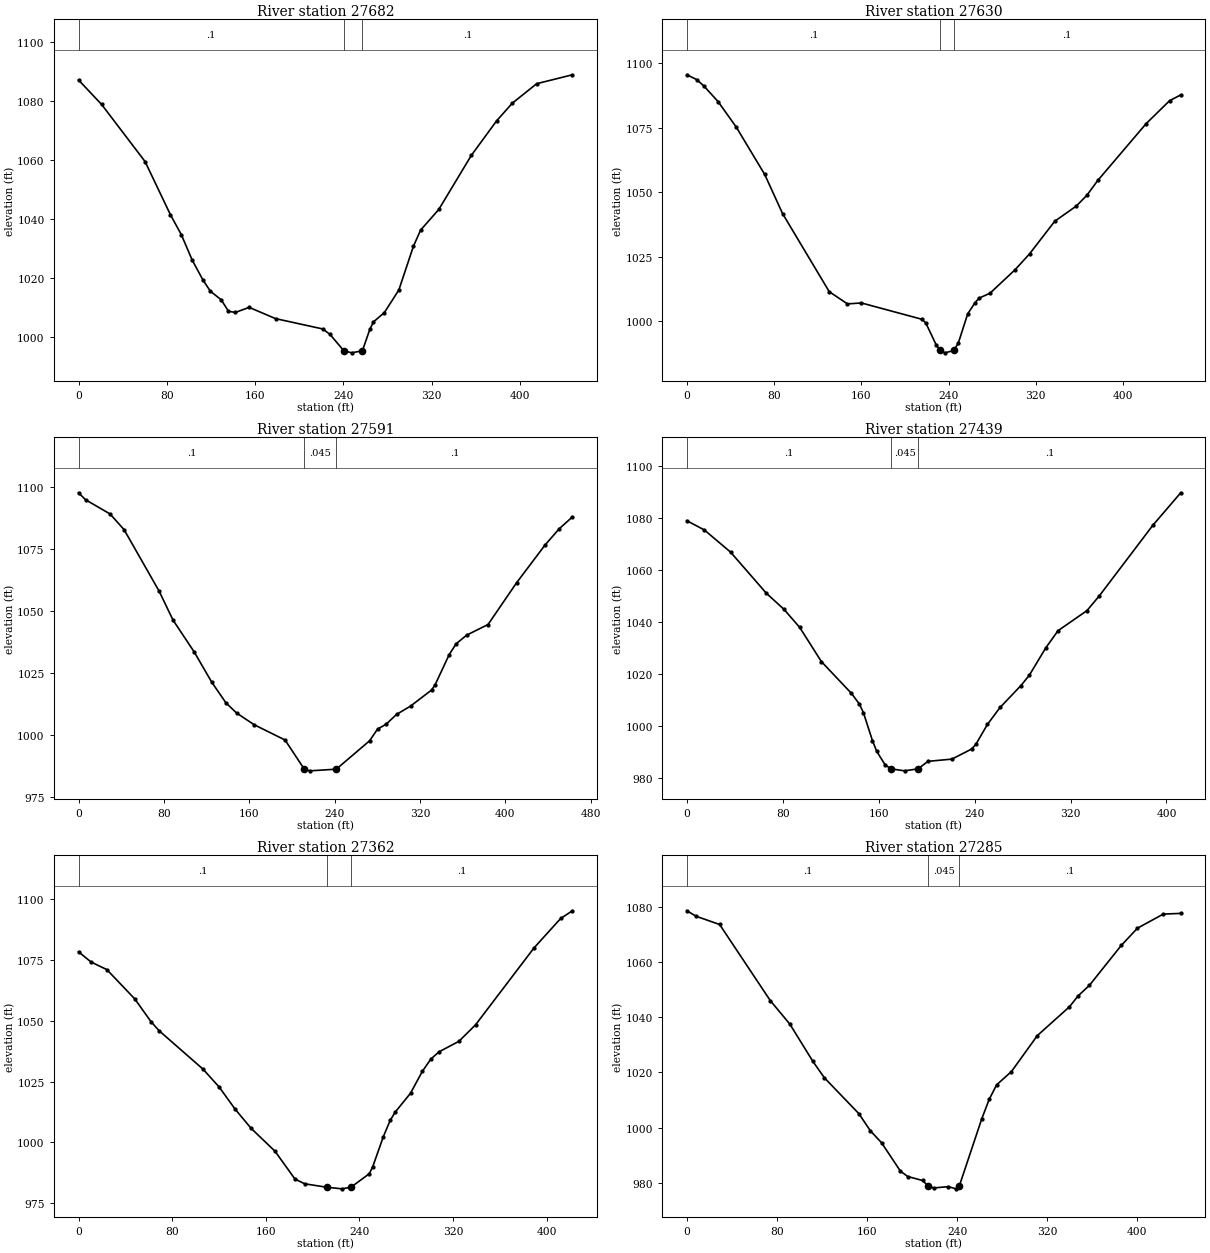
Type RM Length L Ch R = 1 ,27682   ,48.2,51.6,54.8
XS GIS Cut Line= 2
1639368.59626887533414.1085160271639393.06002563533861.067963913
#Sta/Elev= 30
       0 1087.13    20.9 1078.84    60.3 1059.47    83.3 1041.43    93.2 1034.65
     103 1026.07   112.9 1019.22   119.5 1015.51   129.3  1012.6   135.9 1008.72
   142.1 1008.31   154.6 1010.04   178.6 1006.22   221.3 1002.72   227.9 1000.87
   240.4995.3425   247.6  994.62  257.29995.3413     264 1002.58   267.3 1005.11
   277.2 1008.29   290.3 1015.94   303.5 1030.75     310 1036.23   326.5 1043.24
     356 1061.58     379 1073.32   393.1 1079.26   415.2 1085.87   447.6  1088.9
#Mann= 3, -1 ,  0
       0     0.1       0   240.4   0.045       0  257.29     0.1       0
Bank Sta=240.4,257.29
XS Rating Curve= 0 ,0
Exp/Cntr(USF)=0,0
Exp/Cntr=0.3,0.1

Type RM Length L Ch R = 1 ,27630   ,38.2,38.8,41.3
XS GIS Cut Line= 4
1639350.54190191533412.8928960941639360.45964114533578.849732514
1639324.75577992533676.043576951 1639341.2853453533858.529978751
#Sta/Elev= 30
       0 1095.57       9 1093.72    15.5 1091.27    28.7 1085.15    45.3 1075.29
    71.4 1056.93    87.8 1041.75   130.6 1011.48   147.3 1006.74   160.1 1007.11
   215.7 1000.77   219.2  999.33   228.6  990.94  232.38  988.68   236.7  987.77
   244.9  988.68   249.1   991.7   257.6 1002.87   264.4 1007.26   268.1 1008.99
   278.1 1010.89   301.1 1020.01   314.3 1026.12   337.4 1038.77   357.2 1044.67
   366.9 1048.84   376.9 1054.59   421.2 1076.59   442.8 1085.53     453 1087.76
#Mann= 3, -1 ,  0
       0     0.1       0  232.38   0.045       0   244.9     0.1       0
Bank Sta=232.38,244.9
XS Rating Curve= 0 ,0
Exp/Cntr(USF)=0,0
Exp/Cntr=0.3,0.1

Type RM Length L Ch R = 1 ,27591   ,166.3,152.5,130.1
XS GIS Cut Line= 6
1639337.93411858533411.9741560071639336.39048651533504.228236586
1639326.03781693533582.8110846731639278.34926401533672.126522839
  1639284.349252533761.2434705941639302.56214209533860.495240584
#Sta/Elev= 30
       0 1097.56     6.6 1094.74    29.6    1089    42.7 1082.68    75.5 1057.93
    88.6 1046.21   108.4 1033.39     125 1021.09   138.2 1012.84   148.1 1008.77
   164.7 1004.01   193.6  997.86  211.67 986.104   216.9  985.43  241.62986.1022
   272.8  997.52   280.4 1002.31   288.3  1004.2   298.1 1008.18   311.3 1011.55
     331 1018.03   334.3 1020.14   347.5 1032.31     354 1036.67   363.9 1040.16
   383.9 1044.43   410.6 1061.24   437.3 1076.47   450.6 1083.03     463 1087.83
#Mann= 3, -1 ,  0
       0     0.1       0  211.67   0.045       0  241.62     0.1       0
Bank Sta=211.67,241.62
XS Rating Curve= 0 ,0
Exp/Cntr(USF)=0,0
Exp/Cntr=0.3,0.1

Type RM Length L Ch R = 1 ,27439   ,75.1,76.8,76.9
XS GIS Cut Line= 4
1639083.78165393533510.5595503651639153.98128962 533647.69372241
 1639214.3856273533701.5678614271639266.62721665533870.536751982
#Sta/Elev= 30
       0 1079.04    14.6 1075.48    36.5 1066.94    66.2  1051.2    80.9    1045
    94.1 1038.03   112.2 1024.87   137.3 1012.63   143.9 1008.54   147.3 1005.19
   154.8  994.46   158.3  990.42   165.3  985.18   170.2  983.63   181.6  982.86
  192.97983.6294     201  986.51   221.1  987.37   237.4  991.23     241  993.02
   250.7 1000.72   261.2 1007.22   278.7 1015.67   285.6 1019.61   299.3 1030.11
   309.6 1036.76   333.7 1044.47     344 1050.14   388.6 1077.25   411.9 1089.78
#Mann= 3, -1 ,  0
       0     0.1       0   170.2   0.045       0  192.97     0.1       0
Bank Sta=170.2,192.97
XS Rating Curve= 0 ,0
Exp/Cntr(USF)=0,0
Exp/Cntr=0.3,0.1

Type RM Length L Ch R = 1 ,27362   ,65.4,76.8,84.8
XS GIS Cut Line= 4
1639051.23516011533519.8176945181639103.49669931533699.420730653
 1639150.6056924533750.2101138221639204.33938763533906.994731432
#Sta/Elev= 30
       0 1078.42    10.7  1074.2    24.2 1071.08      48 1059.05      62 1049.62
    68.8 1045.96   106.4 1030.12   120.1 1022.82   133.7 1013.74   147.4 1005.81
   167.9  996.35     185  984.89   193.3  982.94  211.99981.5416   225.2  980.87
  232.82981.5405   248.5  987.08   251.5  990.04   260.5 1002.34   266.4 1009.09
   270.8 1012.54   283.8 1020.26   293.8 1029.19   301.1 1034.26     308 1037.22
   325.1 1041.58   339.3 1048.36   389.3 1080.02   412.1 1092.14   422.1 1095.29
#Mann= 3, -1 ,  0
       0     0.1       0  211.99   0.045       0  232.82     0.1       0
Bank Sta=211.99,232.82
XS Rating Curve= 0 ,0
Exp/Cntr(USF)=0,0
Exp/Cntr=0.3,0.1

Type RM Length L Ch R = 1 ,27285   ,141.9,141.4,139.6
XS GIS Cut Line= 6
1639009.69100867533525.4647426751639040.33661668533616.370072678
1639061.00357009533693.7819913331639053.70666867533793.515387669
1639048.23391059533868.3154349181639041.84940892533955.581992671
#Sta/Elev= 30
       0 1078.54     8.4 1076.53    29.1 1073.57    74.1    1046    91.5 1037.47
   111.9    1024   122.1 1018.06   152.7 1005.08     163  998.84     173  994.47
   189.6  984.26   196.2  982.28   209.3  980.85   214.3 978.843   219.2  978.13
   232.3  978.63   238.9  977.82  241.96978.8452   261.9 1003.19   268.5 1010.24
   275.1 1015.49   288.3 1020.32   311.3 1033.35   339.8 1043.77   347.5 1047.72
   357.5 1051.53   385.9 1066.04   400.2 1072.24   423.1 1077.34   438.6 1077.59
#Mann= 3, -1 ,  0
       0     0.1       0   214.3   0.045       0  241.96     0.1       0
Bank Sta=214.3,241.96
XS Rating Curve= 0 ,0
Exp/Cntr(USF)=0,0
Exp/Cntr=0.3,0.1

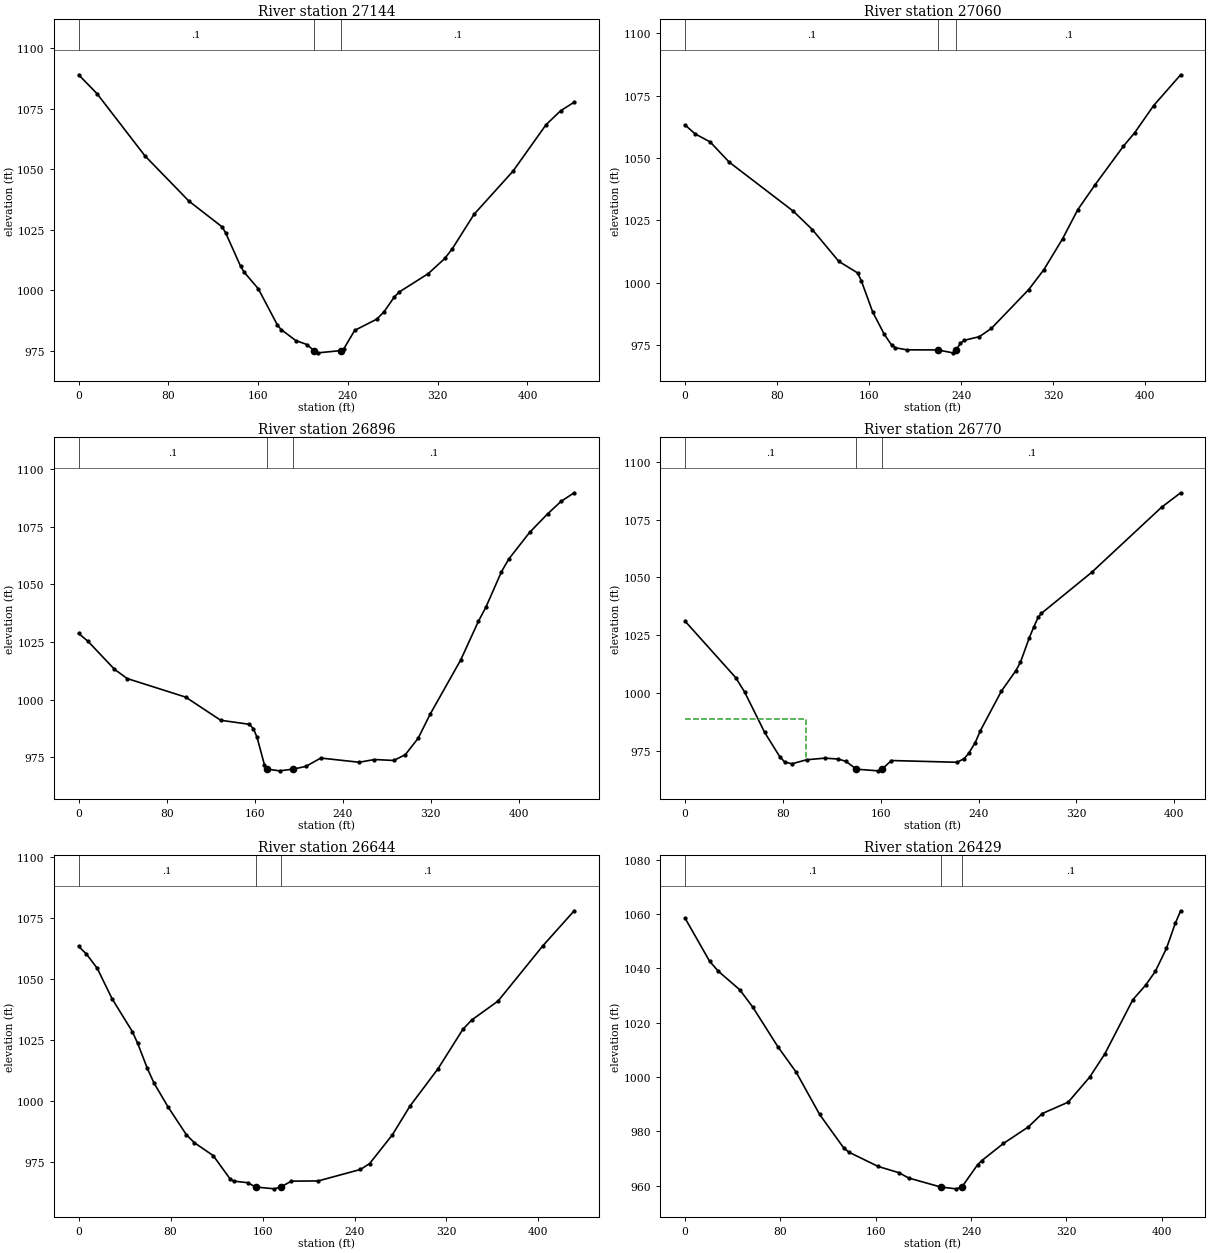
Type RM Length L Ch R = 1 ,27144   ,78.4,83.7,79.2
XS GIS Cut Line= 2
1638913.99648854533520.3548483681638919.71041237533961.959533345
#Sta/Elev= 30
       0 1089.04    16.3 1081.29      59  1055.6    98.3 1036.84   127.9 1026.19
   131.1 1023.65   144.3 1009.96   147.6 1007.43   160.1 1000.64   177.1  985.69
   180.4  983.79   193.5  979.25   203.4   977.6  209.68975.0806   213.2  974.16
  233.76 975.079   236.1  975.66     246  983.43   265.7  988.08   272.2  991.15
   281.1  997.09   285.4  999.21   311.6  1006.9   326.3 1013.15     333 1017.17
   352.4 1031.41   387.1 1049.22   416.6 1068.45   429.7 1074.24   441.6  1077.7
#Mann= 3, -1 ,  0
       0     0.1       0  209.68   0.045       0  233.76     0.1       0
Bank Sta=209.68,233.76
XS Rating Curve= 0 ,0
Exp/Cntr(USF)=0,0
Exp/Cntr=0.3,0.1

Type RM Length L Ch R = 1 ,27060   ,160.1,164,147.6
XS GIS Cut Line= 4
1638841.89656485533531.244584218  1638848.508391 533703.81324679
1638837.26828654533780.5104301551638851.81430408533960.352101494
#Sta/Elev= 30
       0 1063.19     8.7 1059.67    21.8 1056.42    38.3 1048.35    94.1 1028.67
   110.5 1021.36   133.5 1008.62   149.9 1003.97   153.2 1000.73     163  988.34
   172.9  979.53   179.5  975.02   182.8  973.99   192.8  973.16  219.66 973.125
   232.6  971.96  235.63 973.126   239.2  975.77   242.5  976.98   255.7  978.43
   266.2  981.77   298.6  997.31   311.7 1005.23   328.1 1017.71   341.2 1029.29
   356.4 1039.37   380.8 1054.69   390.7 1060.14   407.1 1070.97   430.6 1083.33
#Mann= 3, -1 ,  0
       0     0.1       0  219.66   0.045       0  235.63     0.1       0
Bank Sta=219.66,235.63
XS Rating Curve= 0 ,0
Exp/Cntr(USF)=0,0
Exp/Cntr=0.3,0.1

Type RM Length L Ch R = 1 ,26896   ,122.9,126.1,118.4
XS GIS Cut Line= 4
1638737.09640062533541.531409595 1638701.7650318533665.651768749
1638727.88582648533757.0745501121638806.00557444533969.462608845
#Sta/Elev= 30
       0 1028.74     8.6 1025.29    32.5 1013.23    44.1 1009.18    97.3 1001.11
   129.1  991.07   155.3  989.31   158.8  987.42   162.1  983.77   168.9  971.71
  171.44969.8676   182.6  969.12  195.08969.8642   206.5  971.05   220.1  974.67
     255  972.85   268.9  974.03   286.4  973.62   296.9  976.12   308.6  983.28
   319.6  993.79   347.3 1017.26   363.3 1033.97   370.3 1040.28   384.3 1055.51
   390.9    1061   409.9 1072.59   426.2  1080.6   438.4 1086.03   450.4 1089.79
#Mann= 3, -1 ,  0
       0     0.1       0  171.44   0.045       0  195.08     0.1       0
Bank Sta=171.44,195.08
XS Rating Curve= 0 ,0
Exp/Cntr(USF)=0,0
Exp/Cntr=0.3,0.1

Type RM Length L Ch R = 1 ,26770   ,127.8,126.6,124.8
XS GIS Cut Line= 2
1638555.46108305533650.2600154671638730.75070201534015.744833223
#Sta/Elev= 30
       0 1031.05    41.4 1006.65    48.7 1000.41    65.1  982.95    77.4  972.51
    81.4  970.22    87.3   969.4    99.4  971.14   114.2  971.85   125.1  971.46
   131.5  970.49  140.06967.0756   157.8  966.36  161.12 967.076   168.7  970.82
   222.5  970.06   228.4  971.67   232.3  974.21   237.3  978.58   241.5  983.71
   258.7 1000.82   270.6 1009.73   274.3 1013.31   281.5 1023.89   285.2 1028.56
   288.8 1032.74   291.4 1034.43   332.5 1052.14   389.7  1080.3   405.3 1086.56
#Mann= 3, -1 ,  0
       0     0.1       0  140.06   0.045       0  161.12     0.1       0
#XS Ineff= 2 , 0
           98.93  988.96
Permanent Ineff=
       F       F
Bank Sta=140.06,161.12
XS Rating Curve= 0 ,0
Exp/Cntr(USF)=0,0
Exp/Cntr=0.3,0.1

Type RM Length L Ch R = 1 ,26644   ,212.2,215,215.6
XS GIS Cut Line= 6
1638415.65123406533709.9904756561638467.14981872533780.734428661
1638511.80228847533840.9934944971638571.24278639533921.410328405
 1638611.5415903533988.0499589161638658.02148423534065.980249243
#Sta/Elev= 30
       0 1063.33     6.8 1060.22    16.2 1054.34    29.1 1041.89    46.7 1028.45
    51.4 1023.56    59.8 1013.31    65.6 1007.32    77.8  997.54    93.7  986.18
   100.7  982.88   117.1  977.59   131.7  968.09   134.9  967.13   147.1   966.5
  153.91964.7418   170.3  963.98   175.8964.7408   185.1  967.13   208.4  967.22
   245.1  971.91   253.2  974.35     273  986.16   288.3  997.93   312.7 1013.23
   334.3 1029.38     342 1033.18   364.9 1040.95   403.6 1063.45   431.1 1077.94
#Mann= 3, -1 ,  0
       0     0.1       0  153.91   0.045       0   175.8     0.1       0
Bank Sta=153.91,175.8
XS Rating Curve= 0 ,0
Exp/Cntr(USF)=0,0
Exp/Cntr=0.3,0.1

Type RM Length L Ch R = 1 ,26429   ,100.2,102.6,102.6
XS GIS Cut Line= 3
1638276.19873767533797.0437521351638346.94431043533945.590391749
1638453.27465014534173.364431387
#Sta/Elev= 30
       0  1058.5    20.5  1042.7    27.7 1039.05    45.9 1032.14    56.8 1025.76
      78  1011.1    93.2 1001.83   112.9  986.26   133.1  973.94   137.5  972.36
   162.1   967.1   179.4  964.82   187.6  962.86  214.42959.5528   227.4  958.87
   232.3959.5524   245.5  967.75   249.1  969.29   267.2  975.59     288  981.64
   299.8  986.59   321.5  990.77   339.6 1000.02   352.2  1008.5   375.8 1028.49
   386.6 1033.89   394.6 1038.89     404 1047.39   411.4 1056.61   415.9 1061.23
#Mann= 3, -1 ,  0
       0     0.1       0  214.42   0.045       0   232.3     0.1       0
Bank Sta=214.42,232.3
XS Rating Curve= 0 ,0
Exp/Cntr(USF)=0,0
Exp/Cntr=0.3,0.1

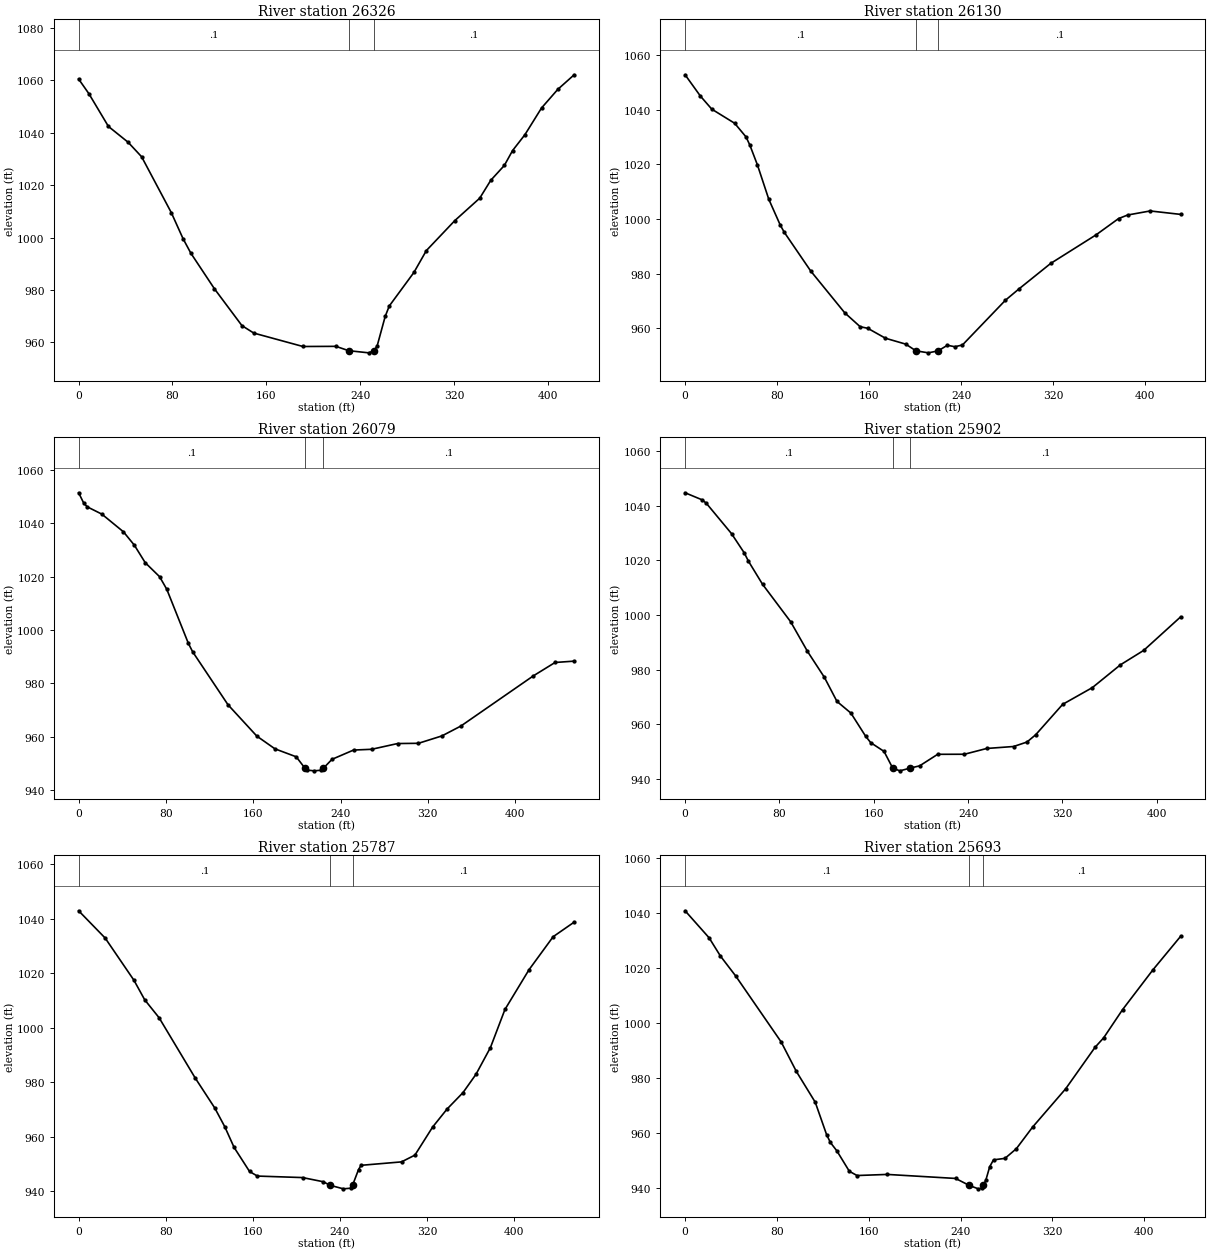
Type RM Length L Ch R = 1 ,26326   ,191.2,196.2,198.1
XS GIS Cut Line= 3
1638226.95191768533823.4207332251638256.76307737533971.151591227
1638352.15878836534225.540153885
#Sta/Elev= 30
       0 1060.54     8.7 1054.98    25.4 1042.45    42.2 1036.41    53.7 1030.87
      79 1009.55      89  999.62    95.7  994.04   115.8  980.46   139.2  966.43
   149.3  963.58   191.2  958.46   219.3  958.52  230.18 956.863   247.3  956.04
  251.85956.8655   254.5  958.74   261.3  969.92   264.8  973.93   285.8  986.73
   296.4  995.07   320.7 1006.53   341.9 1015.07   351.3 1021.89   362.9 1027.58
   369.9 1033.25   380.4 1039.29   394.6 1049.51   408.5 1056.63   422.4 1062.17
#Mann= 3, -1 ,  0
       0     0.1       0  230.18   0.045       0  251.85     0.1       0
Bank Sta=230.18,251.85
XS Rating Curve= 0 ,0
Exp/Cntr(USF)=0,0
Exp/Cntr=0.3,0.1

Type RM Length L Ch R = 1 ,26130   ,50.9,50.6,50.9
XS GIS Cut Line= 4
1638076.19420721533881.052245809 1638097.4323257534051.946295974
1638103.56622422534130.5723600561638202.67037516534280.553959466
#Sta/Elev= 30
       0  1052.8    13.3 1045.01    23.2 1040.22    43.1 1035.05      53 1030.04
    56.3 1027.06    62.9 1019.79    72.8  1007.2    82.7  997.83    86.1  995.24
   109.2     981   138.8  965.69   152.2  960.61   158.8  960.03   174.2  956.39
   191.8  954.24  200.72951.7806   211.5  951.05  220.02951.7805     228  953.82
   234.5  953.29   241.1  953.92   278.5  970.31   290.3  974.46   317.8  983.76
   357.3  994.23   376.8 1000.17   384.7 1001.48   404.3 1002.97   430.8 1001.71
#Mann= 3, -1 ,  0
       0     0.1       0  200.72   0.045       0  220.02     0.1       0
Bank Sta=200.72,220.02
XS Rating Curve= 0 ,0
Exp/Cntr(USF)=0,0
Exp/Cntr=0.3,0.1

Type RM Length L Ch R = 1 ,26079   ,179.7,177.3,171.3
XS GIS Cut Line= 5
1638031.78581226533886.1867902581638049.75883142534048.101817253
1638053.44390543534148.767301843  1638063.548586534186.383535407
1638178.66885105534284.872229081
#Sta/Elev= 30
       0 1051.33     4.8 1047.35     8.1 1046.03    21.3 1043.34    41.1 1036.72
    51.1 1031.71      61  1025.2    74.2 1019.94    80.8 1015.22   100.6  994.96
   104.5  991.85   136.9  972.03   163.3  960.32   179.9  955.56   199.4  952.58
  207.41948.3137   209.2  947.62   215.8  947.33   222.4  947.57   224.3 948.316
   232.2  951.64   251.9   955.1   268.5  955.39   292.3  957.54   311.4  957.63
   332.9  960.39   350.3  964.09   416.6  982.83   436.6  987.86   454.1  988.36
#Mann= 3, -1 ,  0
       0     0.1       0  207.41   0.045       0   224.3     0.1       0
Bank Sta=207.41,224.3
XS Rating Curve= 0 ,0
Exp/Cntr(USF)=0,0
Exp/Cntr=0.3,0.1

Type RM Length L Ch R = 1 ,25902   ,115,114.5,112.5
XS GIS Cut Line= 3
1637819.93375306533992.5860700191637882.90931673534138.165944482
1638013.76763086 534364.71440081
#Sta/Elev= 30
       0 1044.78    14.4  1042.2      18 1040.94    39.4 1029.79    50.2 1022.73
    53.7 1019.72    65.7 1011.23    89.5  997.52   103.8  986.64   118.1  977.16
   128.8  968.31   140.6  964.04     153  955.62   157.4   953.2   168.7     950
  176.05943.8889   182.1  942.87  190.99943.8871   198.9   944.7   214.2  948.93
   236.9  948.95   255.8  951.07   278.6  951.79   289.9  953.42   297.3  956.09
   320.2  967.24   345.4  973.38   369.2  981.73   388.9  987.01420.2431   999.3
#Mann= 3, -1 ,  0
       0     0.1       0  176.05   0.045       0  190.99     0.1       0
Bank Sta=176.05,190.99
XS Rating Curve= 0 ,0
Exp/Cntr(USF)=0,0
Exp/Cntr=0.3,0.1

Type RM Length L Ch R = 1 ,25787   ,88.3,94.2,98.4
XS GIS Cut Line= 6
1637740.11546384534020.9420981711637752.30704051 534131.46057792
  1637786.001855534205.6559675931637852.68151167534280.179768667
 1637902.8618575534335.9204708341637961.76134601534400.632283673
#Sta/Elev= 30
       0 1042.84    24.4 1032.83    50.8 1017.38    60.7 1010.21    73.9 1003.64
   106.9  981.66   125.1  970.52   134.3  963.64   142.8  956.11     157  947.28
   164.2   945.6   205.7  945.05   224.6  943.53  231.17942.2012   243.2  940.92
   250.1  941.16   251.6942.2009   257.1  947.96   259.4  949.54   296.6   950.8
   308.9  953.28   325.2  963.58   338.4  970.15   353.1   976.2     365   982.9
   378.3  992.72   391.6 1006.66   413.7 1021.22   435.9 1033.34   455.2 1038.68
#Mann= 3, -1 ,  0
       0     0.1       0  231.17   0.045       0   251.6     0.1       0
Bank Sta=231.17,251.6
XS Rating Curve= 0 ,0
Exp/Cntr(USF)=0,0
Exp/Cntr=0.3,0.1

Type RM Length L Ch R = 1 ,25693   ,198.9,206.6,210.7
XS GIS Cut Line= 3
1637743.87235798 534027.754241941637724.24361086534189.691405669
1637756.95818939534456.315220698
#Sta/Elev= 30
       0  1040.7    20.9 1030.88    30.8 1024.23      44 1017.04    83.7  993.01
    96.9  982.31   113.4  971.08   123.3  959.28   126.6  956.45   132.2  953.42
   143.1  945.98   149.8  944.44   176.2  944.84   235.7  943.38  247.65940.8257
   255.5   939.6   258.8  939.89  259.89  940.83   262.1  942.87   265.4  947.65
   268.7  950.14   278.7  950.68   288.6  954.19   302.7  962.02   331.6  975.99
   357.1  991.02   364.7  994.52   381.1 1004.73   407.6 1019.23431.7458 1031.42
#Mann= 3, -1 ,  0
       0     0.1       0  247.65   0.045       0  259.89     0.1       0
Bank Sta=247.65,259.89
XS Rating Curve= 0 ,0
Exp/Cntr(USF)=0,0
Exp/Cntr=0.3,0.1

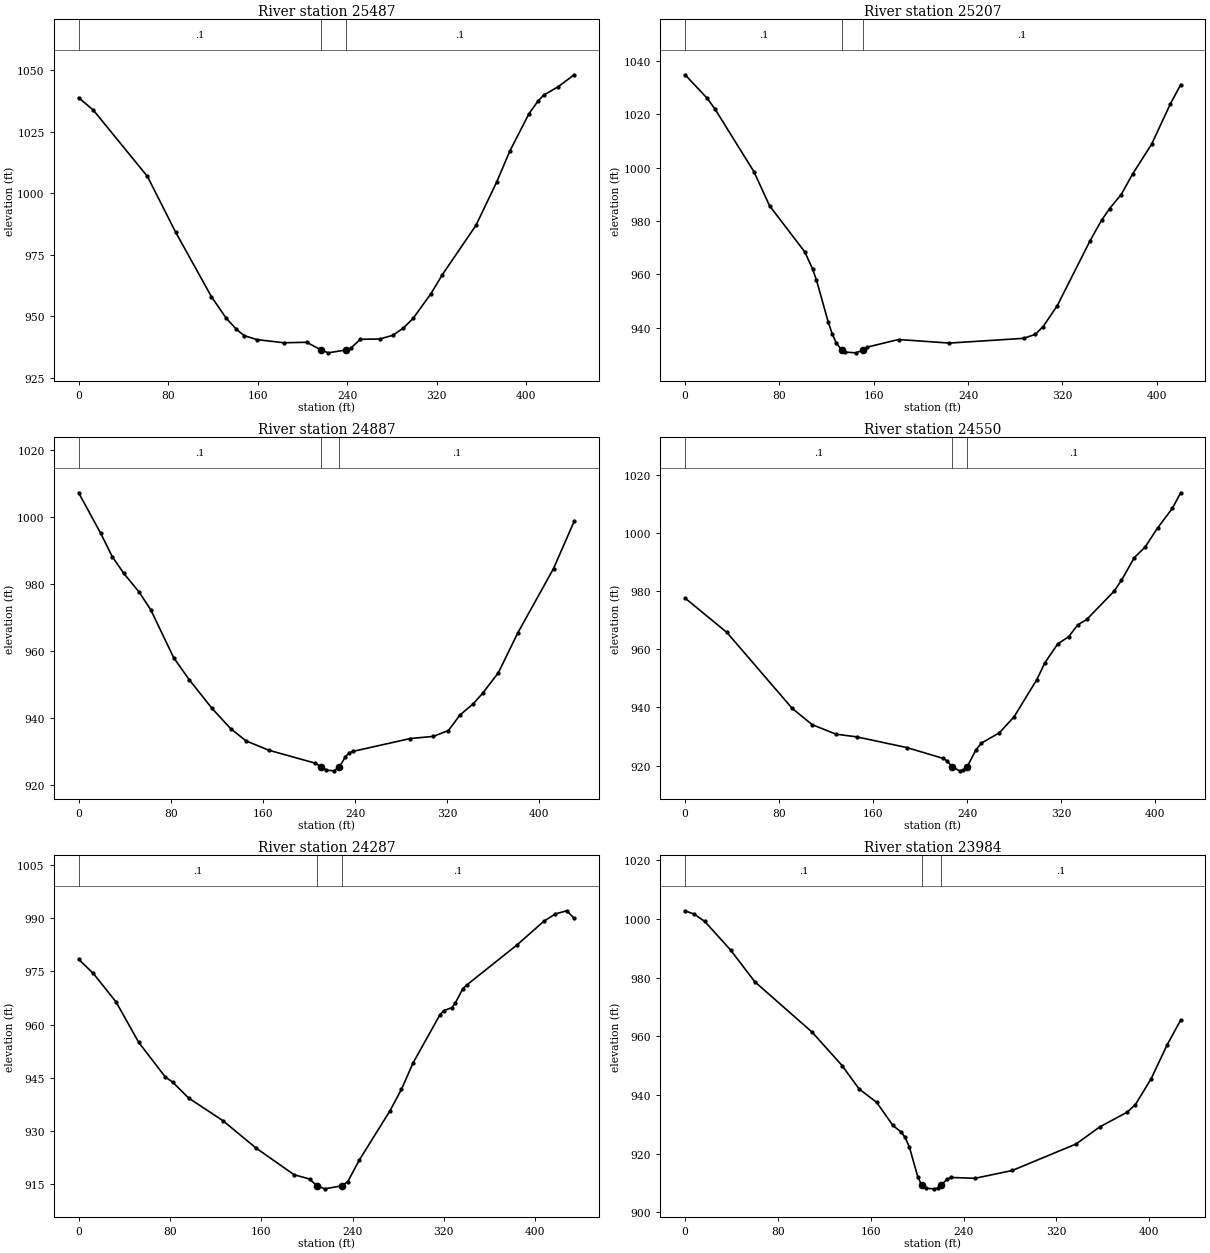
Type RM Length L Ch R = 1 ,25487   ,284.8,279.7,275
XS GIS Cut Line= 6
1637681.80291642534003.2629996691637635.68260184 534096.10270901
1637585.65054968534154.3010834161637521.79536243534231.275995091
1637472.98640493534288.2204350081637416.04262118534354.655997679
#Sta/Elev= 30
       0 1038.91    13.2 1033.81    61.5 1006.87    86.6  984.29   118.7  957.97
   131.7  949.34   140.9  944.77   147.9  942.14   159.6   940.5   183.6  939.23
   203.8  939.44  216.88936.2734     223  935.14  238.52 936.274   243.3  937.07
   251.8  940.66     269  940.76   280.7  942.24   290.3  945.26   298.9  949.12
   314.9   959.2   324.9   966.8   355.1  986.98   373.8 1004.75   385.3 1017.11
   402.6 1032.45   410.6 1037.54   415.6 1039.92   428.6 1043.35   442.9 1048.21
#Mann= 3, -1 ,  0
       0     0.1       0  216.88   0.045       0  238.52     0.1       0
Bank Sta=216.88,238.52
XS Rating Curve= 0 ,0
Exp/Cntr(USF)=0,0
Exp/Cntr=0.3,0.1

Type RM Length L Ch R = 1 ,25207   ,323.3,319.5,317.7
XS GIS Cut Line= 2
1637361.26316118533908.5741786171637303.25280652534324.754396108
#Sta/Elev= 30
       0 1034.77    18.7 1025.98    25.3 1021.96    58.4  998.41    71.7  985.59
   101.5  968.36   108.1  961.96   111.4  957.78   121.4     942   124.7  937.67
     128  934.37  132.88931.4608   135.3  930.82   144.6  930.51  150.85931.4625
   154.5  932.66     181  935.51   224.1  934.17     287  935.95   296.9  937.43
   303.6  940.36   315.6   948.2   343.3  972.45   353.1  980.17   359.9  984.57
   369.8  989.88   379.7  997.72   395.5 1008.68   411.5 1023.85   420.2 1031.06
#Mann= 3, -1 ,  0
       0     0.1       0  132.88   0.045       0  150.85     0.1       0
Bank Sta=132.88,150.85
XS Rating Curve= 0 ,0
Exp/Cntr(USF)=0,0
Exp/Cntr=0.3,0.1

Type RM Length L Ch R = 1 ,24887   ,340.6,337.2,330.8
XS GIS Cut Line= 6
1637014.15202075533934.396339506 1637030.6076965534024.440122679
1637039.24219367534099.9898403441637053.38750659534198.984393001
1637063.99476884534273.2306355831637082.24079534534358.948311925
#Sta/Elev= 30
       0 1007.21    19.2  995.07    29.2  988.13    39.3   983.1    52.6   977.5
    62.6  972.25    82.6  957.89    95.9  951.42   115.7  942.82   132.2  936.66
   145.4  933.07   165.3  930.27     205  926.46  210.79925.2955     215  924.34
   221.6  924.13  226.41925.2958   231.5  928.27   234.8  929.53   238.2  929.95
   287.9  933.78   307.8  934.42     321  936.16     331  940.79   342.6  944.16
   350.9  947.38   364.4  953.45   381.1  965.25   412.3  984.58   430.2  998.69
#Mann= 3, -1 ,  0
       0     0.1       0  210.79   0.045       0  226.41     0.1       0
Bank Sta=210.79,226.41
XS Rating Curve= 0 ,0
Exp/Cntr(USF)=0,0
Exp/Cntr=0.3,0.1

Type RM Length L Ch R = 1 ,24550   ,250.5,262.8,269.3
XS GIS Cut Line= 2
1636661.79478584534151.3224148451636959.74761856534449.450707534
#Sta/Elev= 30
       0  977.56    35.5  965.78    91.1  939.65   108.1  934.06   128.3  930.79
     146  929.86   188.6  926.18   219.5  922.46   222.6   921.7  227.16919.5413
   233.5  918.18   236.5  918.38  239.84919.5425   247.4  925.39     252  927.69
   267.4  931.29   279.9   936.8   299.2  949.56   306.1  955.39     317  961.84
   326.3   964.3   333.9  968.34   341.6  970.22   364.8   979.9   371.1  983.63
     382  991.43   391.3  995.14   401.9 1001.67   414.5 1008.46   421.5 1013.78
#Mann= 3, -1 ,  0
       0     0.1       0  227.16   0.045       0  239.84     0.1       0
Bank Sta=227.16,239.84
XS Rating Curve= 0 ,0
Exp/Cntr(USF)=0,0
Exp/Cntr=0.3,0.1

Type RM Length L Ch R = 1 ,24287   ,308.8,303.6,298.3
XS GIS Cut Line= 6
1636606.90217909534176.851891339  1636621.756152534272.098420009
1636611.50978142534346.6346882581636590.06953558534444.309361666
1636573.47901759534517.4532442541636552.68279934 534602.47177501
#Sta/Elev= 30
       0  978.43    12.8  974.45    32.8  966.37    52.7  954.95    75.9  945.22
    82.6   943.7    96.4  939.26   126.5  932.86   155.5  925.14   188.8  917.62
   202.3  916.41  208.81914.5052   215.7  913.64  230.84914.5073   235.9  915.71
   245.9  921.75   272.8  935.66   282.9  941.75     293  949.16   316.5  962.71
   319.9  963.91     327  964.78     330  966.06   336.7  970.15   340.1  971.17
     384  982.44   407.6  989.15   417.7  991.22   427.6  992.11   434.2  990.02
#Mann= 3, -1 ,  0
       0     0.1       0  208.81   0.045       0  230.84     0.1       0
Bank Sta=208.81,230.84
XS Rating Curve= 0 ,0
Exp/Cntr(USF)=0,0
Exp/Cntr=0.3,0.1

Type RM Length L Ch R = 1 ,23984   ,294.9,296.4,298.2
XS GIS Cut Line= 6
1636212.97055225 534171.16883184 1636253.2493431534248.846826091
1636287.77355225534315.4283858391636327.36271192 534407.54368718
1636350.02670859534479.7850124991636373.63492909534565.059120178
#Sta/Elev= 30
       0  1002.8     7.9 1001.65      17  999.16    39.2  989.42    60.1   978.6
   109.4  961.47   135.3  950.05     150  942.06     165  937.56     179   929.7
   186.2  927.38   189.6  925.59   193.3  922.24   200.5  912.17  203.94909.2087
   207.6  908.25   214.8  908.06   218.3  908.36  220.45909.2096   225.5  911.27
     229  911.94   249.8  911.65   281.9  914.31   336.9  923.34   357.3  929.16
   380.8  934.15     388  936.74   401.6  945.58   415.4  957.15     427  965.54
#Mann= 3, -1 ,  0
       0     0.1       0  203.94   0.045       0  220.45     0.1       0
Bank Sta=203.94,220.45
XS Rating Curve= 0 ,0
Exp/Cntr(USF)=0,0
Exp/Cntr=0.3,0.1