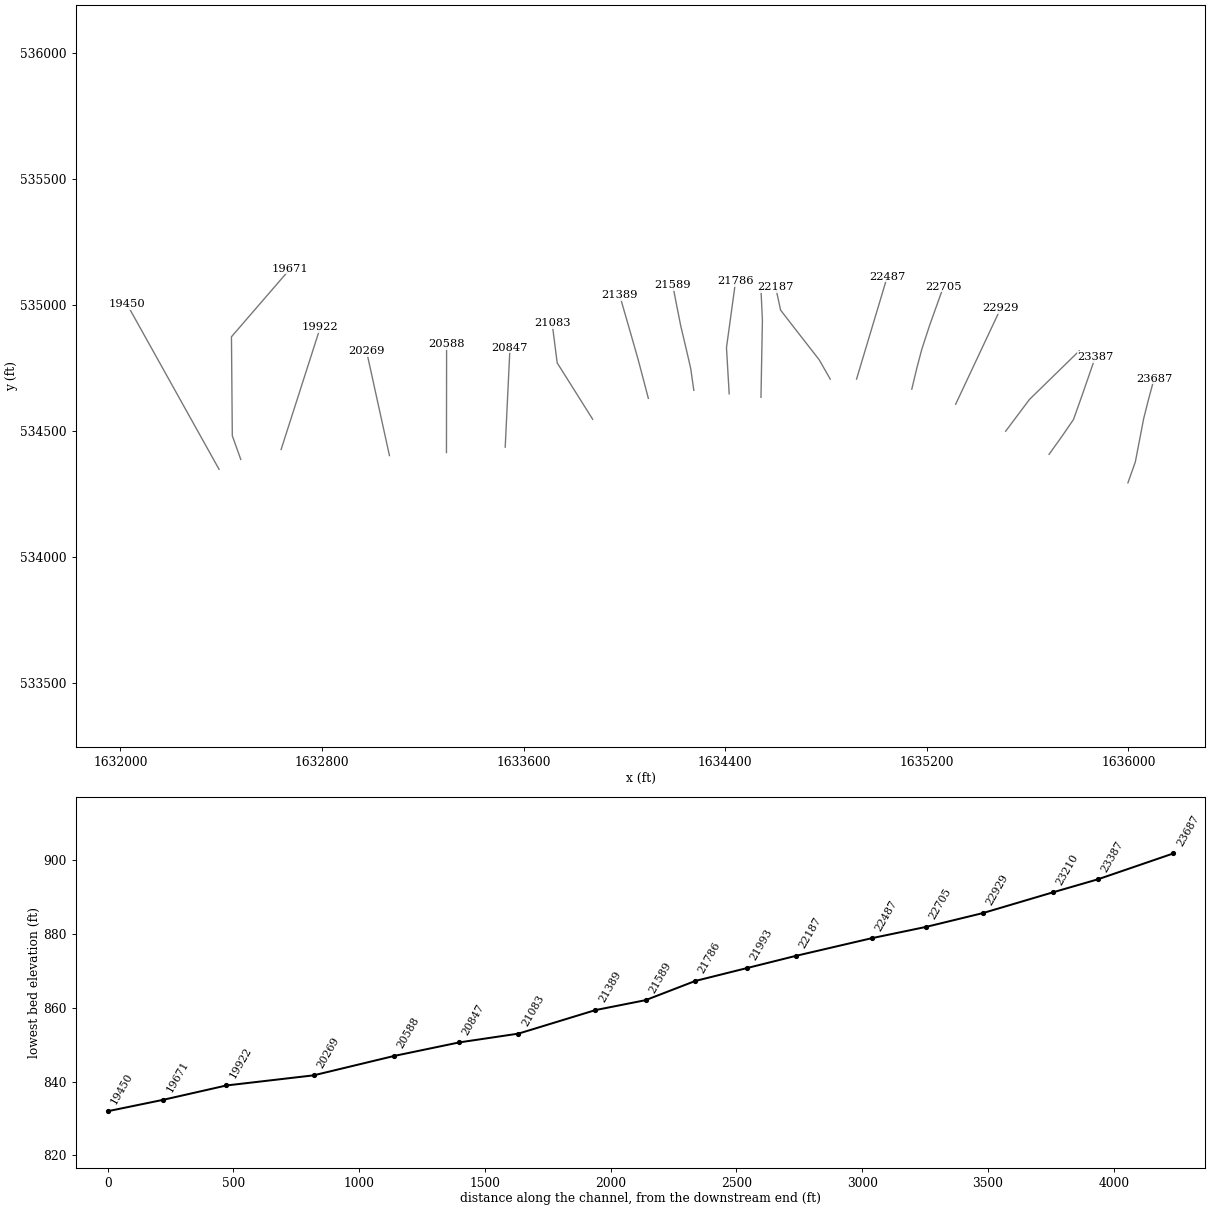
HEC-RAS study LtlGraveCk.prj: LtlGraveCk

--- LtlGraveCk.g01 (geometry) --- (continued)

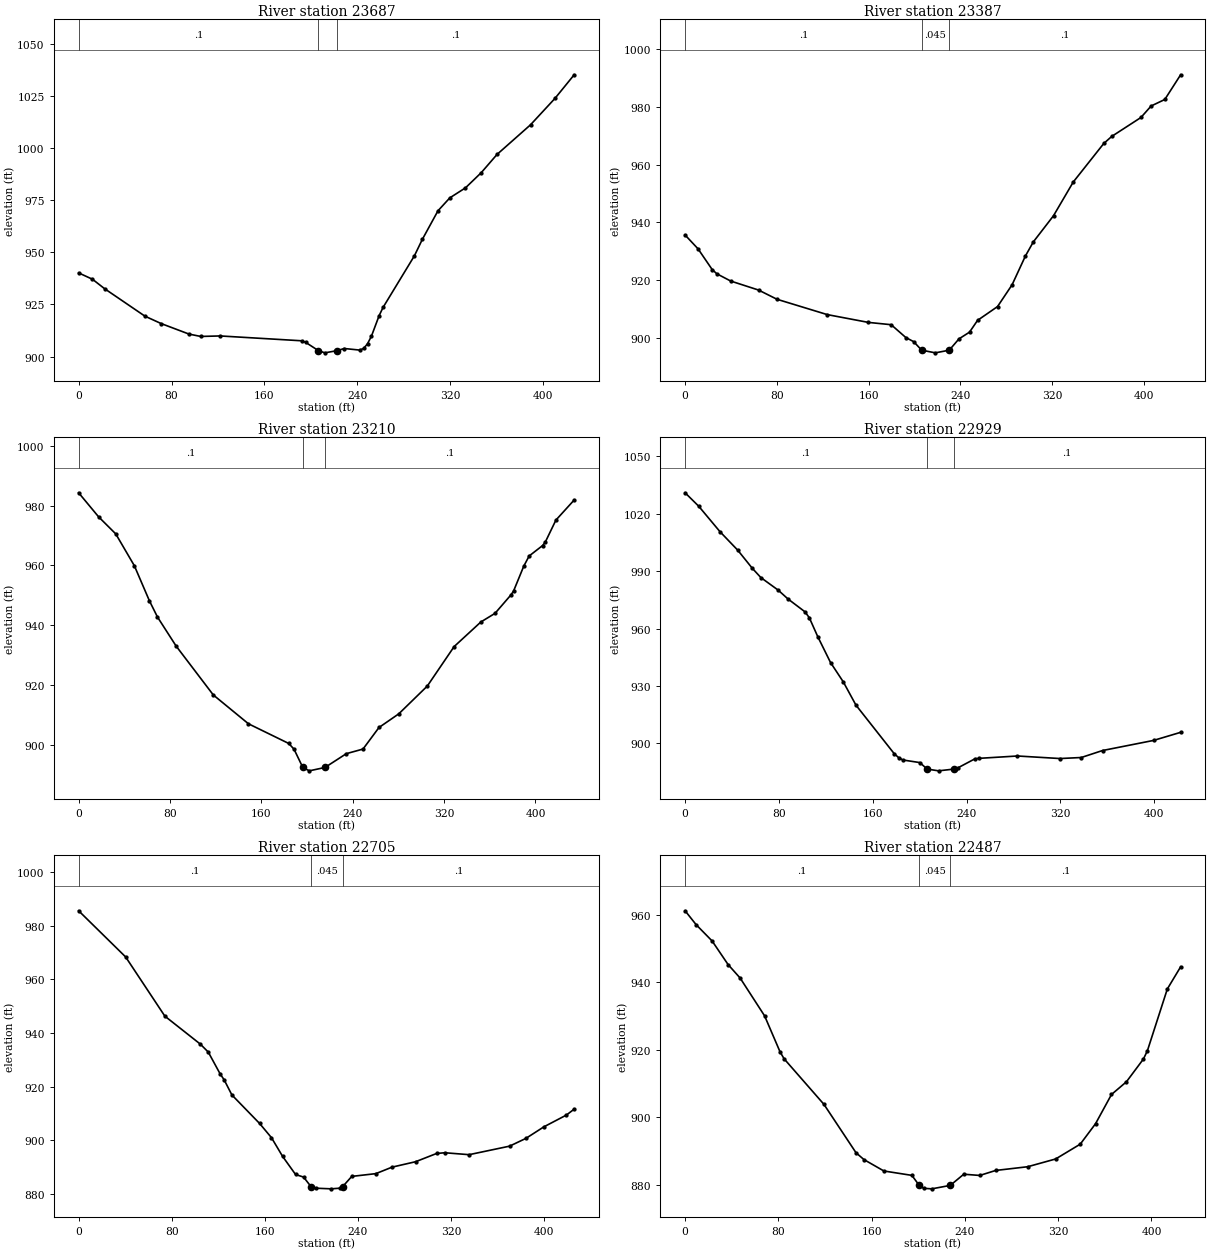
Type RM Length L Ch R = 1 ,23687   ,299.5,300.4,296.8
XS GIS Cut Line= 6
1635997.91717659534293.1584172551636027.35478176534376.294733927
1636041.51715501534449.9455052611636060.40130359534548.146424338
1636078.78807785534621.2056614161636101.69977742534706.471895084
#Sta/Elev= 30
       0  940.14    11.9   937.1    22.3  932.58    57.1  919.37    71.1  915.81
    95.1  910.76   105.2  909.63   121.9  909.87     192  907.55   195.4  906.84
  206.55902.8064   212.1  901.76  222.53 902.806   228.8  903.84   242.1  903.08
   245.5  903.87   248.8  906.11   252.2  909.77   258.8   919.6   262.2  923.57
   289.2  948.35     296  956.21   309.5  969.96   319.7  976.17   333.2  980.98
   346.8  988.28   360.4  997.04   389.2 1011.24   410.2 1023.88   426.8 1035.26
#Mann= 3, -1 ,  0
       0     0.1       0  206.55   0.045       0  222.53     0.1       0
Bank Sta=206.55,222.53
XS Rating Curve= 0 ,0
Exp/Cntr(USF)=0,0
Exp/Cntr=0.3,0.1

Type RM Length L Ch R = 1 ,23387   ,178.5,177.4,170.4
XS GIS Cut Line= 6
1635685.08217233534406.5249884281635738.35175084534481.088487595
1635782.13906483534545.3265480851635815.67869592534639.538301915
1635840.21178333534710.4125040021635868.73403601534793.127889752
#Sta/Elev= 30
       0  935.58    11.3  930.78    23.6  923.61    27.7  922.13    39.8  919.62
      64  916.51    80.1  913.31   123.9     908   159.7   905.3   179.6   904.5
   192.4  900.05   199.2  898.63  206.21895.6693   218.1  894.75  230.23 895.668
   238.7  899.59   247.9  901.92   254.9     906   272.3  910.78     285  918.33
   296.6   928.3   303.5  933.19   321.1  942.26   338.3  953.94   364.9  967.29
   371.8  969.73   397.3   976.3   406.2  980.29   418.1  982.54   431.9   991.1
#Mann= 3, -1 ,  0
       0     0.1       0  206.21   0.045       0  230.23     0.1       0
Bank Sta=206.21,230.23
XS Rating Curve= 0 ,0
Exp/Cntr(USF)=0,0
Exp/Cntr=0.3,0.1

Type RM Length L Ch R = 1 ,23210   ,277.6,280.6,284.6
XS GIS Cut Line= 3
1635512.74385556534498.2027194321635607.06894744534624.271832621
1635804.78885158534817.456876572
#Sta/Elev= 30
       0  984.33    17.5  976.27    32.5  970.57    48.8   959.9      62  948.15
      69  942.76    85.4     933   117.9  916.66   148.7     907     184  900.41
   188.6   898.5  196.29892.3839     202  891.25  215.75892.3864   234.4     897
     249  898.54     263  905.76   280.3  910.32   305.3  919.63   328.8  932.85
   352.2  941.08   364.6  943.97   378.5  950.12   380.8  951.41   389.8   959.8
   394.5  963.18   406.3  966.68   408.7  967.89   417.9  975.18   433.9  981.91
#Mann= 3, -1 ,  0
       0     0.1       0  196.29   0.045       0  215.75     0.1       0
Bank Sta=196.29,215.75
XS Rating Curve= 0 ,0
Exp/Cntr(USF)=0,0
Exp/Cntr=0.3,0.1

Type RM Length L Ch R = 1 ,22929   ,222.2,224.1,225
XS GIS Cut Line= 2
1635314.43496419534605.5217840071635493.93242034534987.960371244
#Sta/Elev= 30
       0 1030.96    11.6 1023.94    29.7 1010.65    44.9 1000.94    57.2  991.55
    64.6  986.63    79.4  980.05    87.7  975.46   102.2  968.73   105.9  965.65
   113.1  955.75     124  942.22   134.9  932.07   145.7  919.92   178.3  894.55
     182  892.53   185.6  891.27   200.1  889.91  206.41886.5057   216.1  885.59
  229.15886.5081   232.7  887.19   247.1  891.87   250.8  892.13   283.4  893.35
   319.7  892.02   337.8  892.56   355.9  896.21   399.4  901.49   422.5  905.72
#Mann= 3, -1 ,  0
       0     0.1       0  206.41   0.045       0  229.15     0.1       0
Bank Sta=206.41,229.15
XS Rating Curve= 0 ,0
Exp/Cntr(USF)=0,0
Exp/Cntr=0.3,0.1

Type RM Length L Ch R = 1 ,22705   ,216.6,217.5,217.4
XS GIS Cut Line= 6
1635140.35865202534665.3446934121635160.84745618534750.885204737
1635180.08068543534823.6560565721635211.11179135534918.759540905
1635236.33746269534989.389977072 1635265.7681781535071.792043243
#Sta/Elev= 30
       0  985.58    40.4  968.36    74.1  946.28   104.6  935.84   111.4  932.88
   121.6  924.74     125  922.56   131.7  916.89   155.5  906.26   165.7  900.96
   175.3  893.96   186.4  887.23   193.3  886.26  199.61882.7418   203.7  882.12
     217  881.88   224.4  882.12  226.95882.7425   234.7  886.52   255.4  887.55
   269.3  889.97   289.5  891.99   307.6  895.07   314.6  895.34   335.5  894.62
   370.3   897.8   384.3  900.69   399.8  905.01   419.1  909.39   425.8   911.6
#Mann= 3, -1 ,  0
       0     0.1       0  199.61   0.045       0  226.95     0.1       0
Bank Sta=199.61,226.95
XS Rating Curve= 0 ,0
Exp/Cntr(USF)=0,0
Exp/Cntr=0.3,0.1

Type RM Length L Ch R = 1 ,22487   ,288.3,300,311.5
XS GIS Cut Line= 6
1634921.17425135534705.3570679281634946.31822993534789.166611582
1634967.86936793534861.0034101751634996.60421859534956.786026999
1635018.15535659535028.6231536721635043.08706525535112.496345505
#Sta/Elev= 30
       0   961.2     9.5  957.07    23.2  952.24    36.9  945.25    47.2  941.27
    68.2  930.05    81.4  919.42    84.9  917.34   119.1  903.83   146.6  889.49
   153.4  887.47   170.5  884.09   194.5  882.79  200.81879.8246   204.8  878.95
   211.6   878.8  227.43879.8235     239  883.13   252.7  882.77   266.4  884.25
   293.8  885.35   317.8  887.65   338.9  892.04     352  898.09   365.7  906.76
   378.5  910.52   393.1  917.28   396.5  919.73   413.6  938.04     425  944.59
#Mann= 3, -1 ,  0
       0     0.1       0  200.81   0.045       0  227.43     0.1       0
Bank Sta=200.81,227.43
XS Rating Curve= 0 ,0
Exp/Cntr(USF)=0,0
Exp/Cntr=0.3,0.1

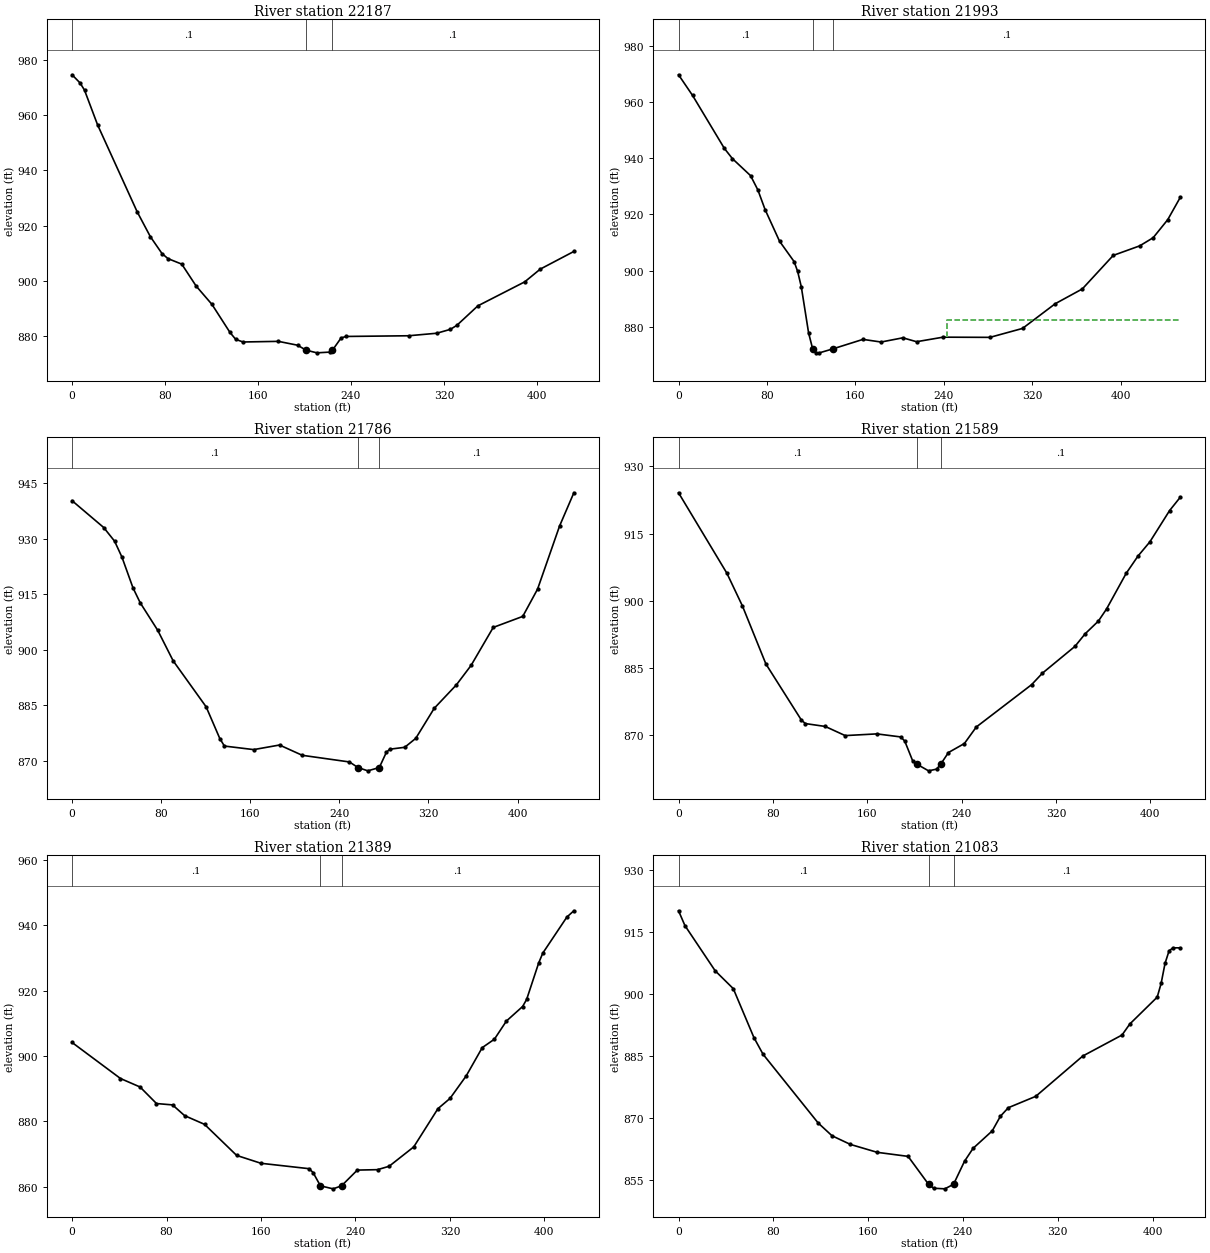
Type RM Length L Ch R = 1 ,22187   ,199.2,194.9,186.8
XS GIS Cut Line= 6
1634816.80175668534705.1700604261634773.09252651534781.786705092
  1634727.047343534840.9883583341634665.65376501   534919.923896
1634619.82052334534979.290575176 1634600.1050116535070.820903927
#Sta/Elev= 30
       0   974.5     6.9  971.54    10.7  968.95      22  956.36      56  925.01
    67.4  915.99    77.4  909.91    82.5  908.09    94.4  906.09   106.8  898.15
   120.4  891.53   135.9   881.4   140.8  878.92   147.1  877.96   177.5  878.19
   194.1  876.79  201.22875.0222   210.7  874.04   221.9  874.31  224.09875.0201
   231.5  879.41   235.7  879.96   289.6  880.21   313.8  881.12   325.5  882.52
   331.1  883.97   349.2  891.02   389.5  899.68   402.9  904.29   431.8  910.67
#Mann= 3, -1 ,  0
       0     0.1       0  201.22   0.045       0  224.09     0.1       0
Bank Sta=201.22,224.09
XS Rating Curve= 0 ,0
Exp/Cntr(USF)=0,0
Exp/Cntr=0.3,0.1

Type RM Length L Ch R = 1 ,21993   ,206.2,206.6,204
XS GIS Cut Line= 3
1634541.93005652534632.8880669761634547.64398036534939.081826779
1634540.75099287535086.736874456
#Sta/Elev= 30
       0  969.73    12.7  962.37    41.5   943.5    48.8  939.85    65.2  933.81
    71.8  928.72    78.3  921.76    91.4  910.48   104.6  903.21   107.8  899.71
   111.1  894.24   117.7  877.82  121.37872.1484   124.3  870.79   127.5  870.73
  139.72872.1492   166.9  875.52   183.3  874.58     203  876.08   215.4  874.69
   239.4  876.31   281.8  876.24   311.3  879.42   340.9  888.22   365.4  893.48
   393.4  905.42   417.3  908.81   429.5  911.71   442.7  918.14   454.1  926.12
#Mann= 3, -1 ,  0
       0     0.1       0  121.37   0.045       0  139.72     0.1       0
#XS Ineff= 2 , 0
                           242.6          882.29
Permanent Ineff=
       F       F
Bank Sta=121.37,139.72
XS Rating Curve= 0 ,0
Exp/Cntr(USF)=0,0
Exp/Cntr=0.3,0.1

Type RM Length L Ch R = 1 ,21786   ,193.1,197.3,199.7
XS GIS Cut Line= 3
1634415.83008227534646.7684177161634405.06797609534830.245182299
 1634441.3134082535094.565960477
#Sta/Elev= 30
       0  940.25    28.4     933    38.2   929.3    44.8  924.99    54.7  916.69
    61.2  912.65    76.9  905.22    90.8  896.95   120.4  884.52   132.7  875.93
   136.8  873.92   163.1  872.96   186.3   874.2   206.7  871.42   249.1  869.62
  256.67868.1192   265.6  867.22  275.91868.1205   282.2  872.21   285.3  873.07
   298.7  873.58   308.6  875.99   325.2  884.12   345.1  890.46   358.3  895.72
   378.2  905.99   404.7  908.97     418  916.34   437.8  933.43   450.6  942.39
#Mann= 3, -1 ,  0
       0     0.1       0  256.67   0.045       0  275.91     0.1       0
Bank Sta=256.67,275.91
XS Rating Curve= 0 ,0
Exp/Cntr(USF)=0,0
Exp/Cntr=0.3,0.1

Type RM Length L Ch R = 1 ,21589   ,199.5,199.4,200
XS GIS Cut Line= 6
1634275.48755059 534660.762012751634263.10404517534747.587298423
1634246.28124417534820.6678609251634223.31442659534918.025605842
1634208.68879968534991.7249335051634191.98902993535077.790378168
#Sta/Elev= 30
       0  924.11      41  906.15    54.2  898.83    74.1  885.88   104.2  873.35
   107.6  872.58   124.4  871.94   141.3   869.9   168.2  870.28   188.4   869.6
   191.8  868.69   198.5  864.29  201.84863.5557     212  862.03   218.8  862.41
  222.41863.5558   228.9  866.12   242.4  868.13   252.5  871.82   299.4  881.27
   308.5  883.82   336.2  889.83   344.8  892.63     356  895.46   362.9  898.15
   379.6  906.13   389.6  909.98   399.7  913.16   416.4  920.14   425.5  923.13
#Mann= 3, -1 ,  0
       0     0.1       0  201.84   0.045       0  222.41     0.1       0
Bank Sta=201.84,222.41
XS Rating Curve= 0 ,0
Exp/Cntr(USF)=0,0
Exp/Cntr=0.3,0.1

Type RM Length L Ch R = 1 ,21389   ,302.8,306.1,308.5
XS GIS Cut Line= 6
1634095.00950307534628.8790828151634072.88520348534713.564937056
1634053.63327348534786.0693852311634026.26718648534882.252591804
1634005.47884223534954.3141274761633981.22659415 535038.38580972
#Sta/Elev= 30
       0  904.14      41  893.11    57.6  890.51    71.5  885.45    85.1  885.03
    95.3  881.75   112.2  879.08   139.4  869.57     160  867.16   200.7  865.51
   204.1  864.34  210.35860.2587   221.1  859.34  228.22 860.256   241.6  865.08
   258.7  865.21   268.5  866.24   289.4  872.18   309.9  883.89   320.1  887.01
   333.8   893.9   347.4  902.56   357.7  905.14   367.9  910.71   381.6  915.15
     385  917.31   395.2  928.47   398.7   931.5   419.1  942.53     425  944.45
#Mann= 3, -1 ,  0
       0     0.1       0  210.35   0.045       0  228.22     0.1       0
Bank Sta=210.35,228.22
XS Rating Curve= 0 ,0
Exp/Cntr(USF)=0,0
Exp/Cntr=0.3,0.1

Type RM Length L Ch R = 1 ,21083   ,241.2,235.7,228.8
XS GIS Cut Line= 3
1633874.15856654534545.8186122341633733.27042888534769.937140409
1633713.29456577534927.336162481
#Sta/Elev= 30
       0  920.13     5.4  916.55    30.9  905.64    46.2  901.32    63.6  889.51
    71.3  885.48   117.8  868.88   129.5  865.79     145   863.7   167.6  861.79
   193.7  860.81  210.95854.0695   215.2  853.12   224.7  852.97  232.04 854.067
   241.3  859.63   248.5  862.74   264.7  866.97   271.6  870.51   278.3  872.57
   301.4  875.31   341.1  885.05   374.2  890.12   380.8  892.79   403.9  899.27
   407.2  902.58   410.5  907.43   413.9  910.45   417.2  911.18   423.4  911.18
#Mann= 3, -1 ,  0
       0     0.1       0  210.95   0.045       0  232.04     0.1       0
Bank Sta=210.95,232.04
XS Rating Curve= 0 ,0
Exp/Cntr(USF)=0,0
Exp/Cntr=0.3,0.1

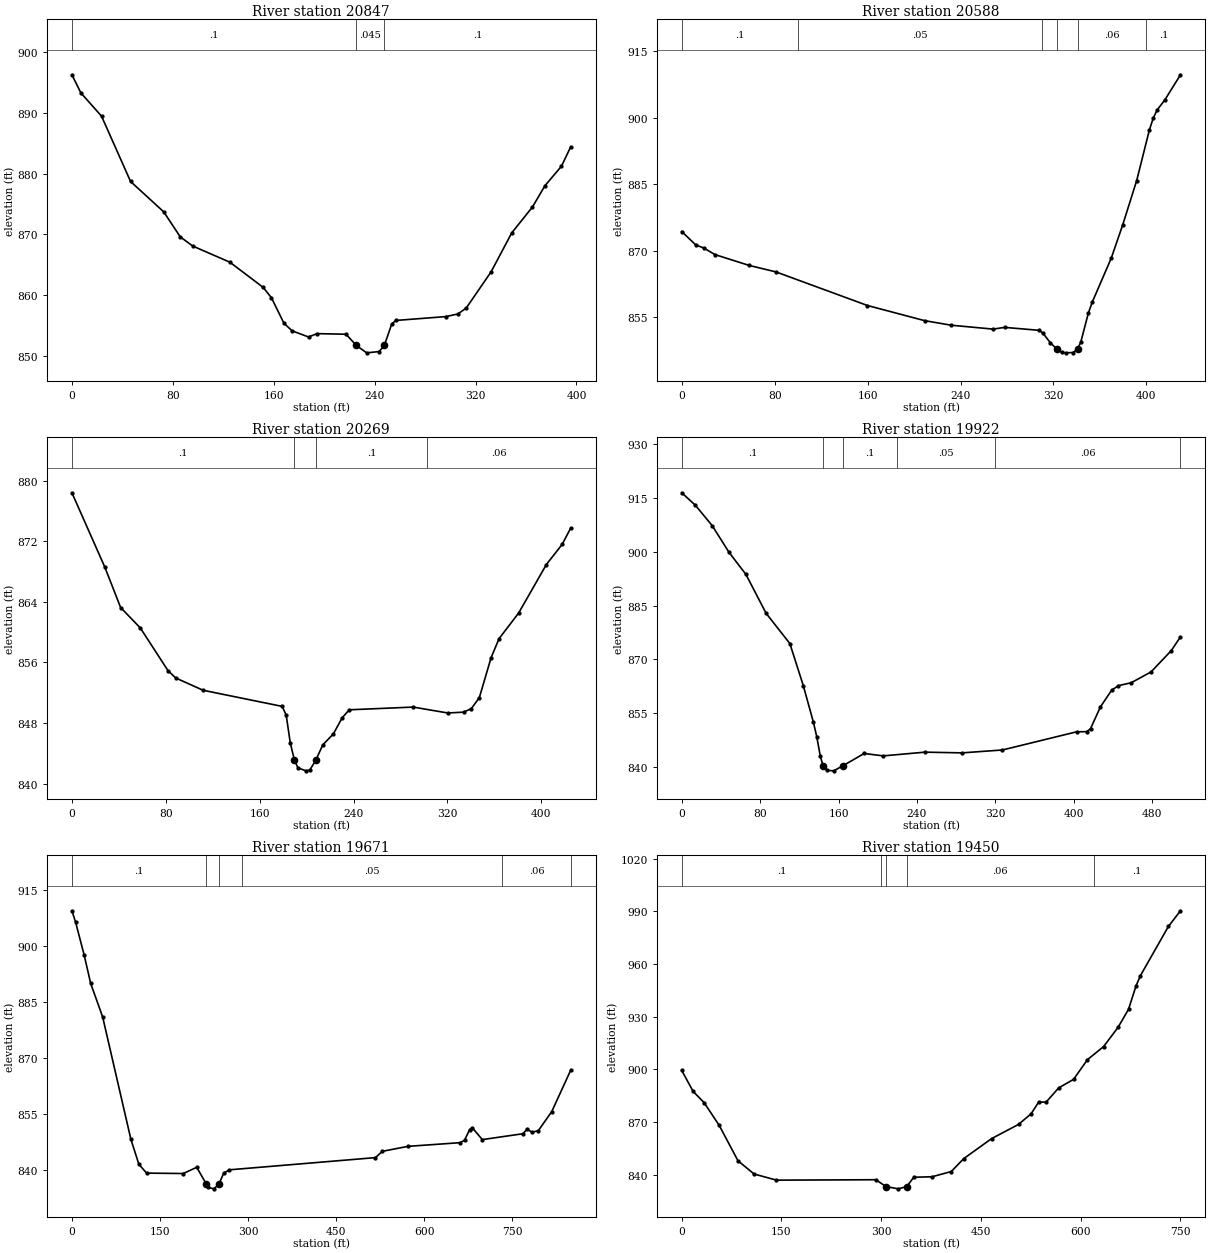
Type RM Length L Ch R = 1 ,20847   ,258.7,258.9,258.3
XS GIS Cut Line= 2
1633527.08066749534435.0639455151633545.99273675534829.980925708
#Sta/Elev= 30
       0  896.19     7.1  893.22    23.5   889.4    46.5  878.69    72.8  873.71
    85.9  869.61    95.8   868.1   125.2  865.46   151.6  861.33   158.2  859.62
   168.1  855.44   174.6   854.2   187.6  853.19   194.3  853.74   217.3  853.64
  225.54851.7983   233.7  850.59   243.6   850.8  247.69851.7995   253.5  855.28
   256.7   855.9   296.2  856.53     306  856.96   312.6  857.93   332.3  863.86
   348.7  870.26   365.1   874.5     375  877.99   388.1  881.19   395.4  884.35
#Mann= 3, -1 ,  0
       0     0.1       0  225.54   0.045       0  247.69     0.1       0
Bank Sta=225.54,247.69
XS Rating Curve= 0 ,0
Exp/Cntr(USF)=0,0
Exp/Cntr=0.3,0.1

Type RM Length L Ch R = 1 ,20588   ,317.5,319.4,321.3
XS GIS Cut Line= 2
1633293.98653012534413.5390840321633294.56412924534842.935383379
#Sta/Elev= 30
       0  874.31    12.2  871.26    18.8  870.62    28.6  869.11    58.2  866.65
    81.1   865.2   159.9  857.61   209.1  854.19     232  853.16   268.1  852.28
     278  852.67   307.5  852.01   310.8  851.44   317.3  849.21  322.81847.8137
   327.2  847.02   330.5  846.92     337  846.99  340.85847.8155   343.6  849.37
   350.1  855.92   353.4  858.35   369.8  868.31   379.7  875.85   391.7  885.83
   402.6  897.24   405.9  899.88   409.2  901.74   415.8  903.99   429.4  909.72
#Mann= 6, -1 ,  0
       0     0.1       0     100    0.05       0     310    0.06       0
  322.81   0.045       0  340.85    0.06       0     400     0.1       0
Bank Sta=322.81,340.85
XS Rating Curve= 0 ,0
Exp/Cntr(USF)=0,0
Exp/Cntr=0.3,0.1

Type RM Length L Ch R = 1 ,20269   ,350.8,347.4,340.2
XS GIS Cut Line= 6
1633067.77793015534401.6364563311633049.01779706534487.101508503
1633032.93744864534560.3575955831633011.49720282534658.031940912
 1632995.4168544534731.2876999131632976.65737747534816.753080165
#Sta/Elev= 30
       0   878.4    28.1  868.56    41.5  863.25    58.3  860.55    81.8  854.93
    88.5  853.94   111.8  852.32   179.2  850.19   182.6  849.04   186.1  845.36
  189.61843.0948   192.6  842.08   199.4  841.68   202.7  841.78  207.89843.0938
   213.7  845.09   222.9  846.58   230.2  848.66   236.3  849.74   290.8   850.1
   320.3  849.32   333.7  849.43   340.4   849.9   347.2  851.35   357.2  856.62
     364  859.14   380.7  862.52   404.3  868.92   417.7  871.57     425  873.72
#Mann= 4, -1 ,  0
       0     0.1       0  189.61   0.045       0  207.89     0.1       0
   302.5    0.06       0
Bank Sta=189.61,207.89
XS Rating Curve= 0 ,0
Exp/Cntr(USF)=0,0
Exp/Cntr=0.3,0.1

Type RM Length L Ch R = 1 ,19922   ,247.4,250.3,254.1
XS GIS Cut Line= 2
1632637.88038257534425.7495190821632793.20448731534910.399613681
#Sta/Elev= 30
       0  916.46    13.8  913.01      31  907.32    48.2  899.87    65.5  893.69
    86.1  882.85   110.3  874.43     124  862.72   134.4  852.42   137.8  848.38
   141.3  843.15  144.17840.3289   148.2  839.06     155  838.93  164.37840.3265
   186.1  843.77   205.6   843.1   248.1  844.14     286  843.94   327.3  844.75
   403.1  849.82   413.4  849.85   417.2  850.72   427.2  856.74   438.6  861.39
   445.6  862.68   458.7   863.5   478.9  866.51   499.6  872.47   508.9  876.29
#Mann= 6, -1 ,  0
       0     0.1       0  144.17   0.045       0  164.37     0.1       0
     220    0.05       0     320    0.06       0  508.93     0.1       0
Bank Sta=144.17,164.37
XS Rating Curve= 0 ,0
Exp/Cntr(USF)=0,0
Exp/Cntr=0.3,0.1

Type RM Length L Ch R = 1 ,19671   ,209.6,221.5,226.6
XS GIS Cut Line= 4
1632477.84166705534386.3390701771632444.25011011534480.395429604
1632440.89095442534873.4166457811632673.79241586535143.268819851
#Sta/Elev= 30
       0  909.32     6.2  906.33      21  897.41    31.9  889.94    52.3     881
   100.4  848.32   114.1  841.59   127.3  839.26   189.6  839.15   212.6  840.81
  228.65836.4175   232.3  835.44   242.1  835.06  250.67836.4164   258.5  839.25
   268.3  840.14     517   843.4   528.7  845.08   572.5  846.41   661.3  847.39
   668.7  848.03   677.3  850.87   681.7   851.4     699  848.21   768.3  849.78
   775.3  851.02   783.4  850.18   794.3  850.59   817.2  855.68   849.4   866.7
#Mann= 6, -1 ,  0
       0     0.1       0  228.65   0.045       0  250.67     0.1       0
  289.87    0.05       0  732.91    0.06       0  849.37     0.1       0
Bank Sta=228.65,250.67
XS Rating Curve= 0 ,0
Exp/Cntr(USF)=0,0
Exp/Cntr=0.3,0.1

Type RM Length L Ch R = 1 ,19450   ,259,262.7,260
XS GIS Cut Line= 2
1632391.62333758534347.1489204161632026.47067234535002.557520233
#Sta/Elev= 30
       0  899.39    17.1  887.47    33.7  881.03    56.2   868.2    84.6  847.94
   108.8  840.41   142.5  836.91   292.1  837.15  307.22833.2554   325.8  831.96
  338.41833.2524   349.1  838.57   376.5  838.83   405.5  841.83   424.2  849.17
     466  860.54   506.7  868.67   525.6  874.72   536.9  881.34   548.2  881.37
     567  889.44   589.5  894.33   610.4  905.59   634.6  912.97   656.3   923.9
   672.1  934.19   683.4  947.52     690  953.38   732.2  981.46   750.3  990.35
#Mann= 5, -1 ,  0
       0     0.1       0     300    0.06       0  307.22   0.045       0
  338.41    0.06       0     620     0.1       0
Bank Sta=307.22,338.41
XS Rating Curve= 0 ,0
Exp/Cntr(USF)=0,0
Exp/Cntr=0.3,0.1