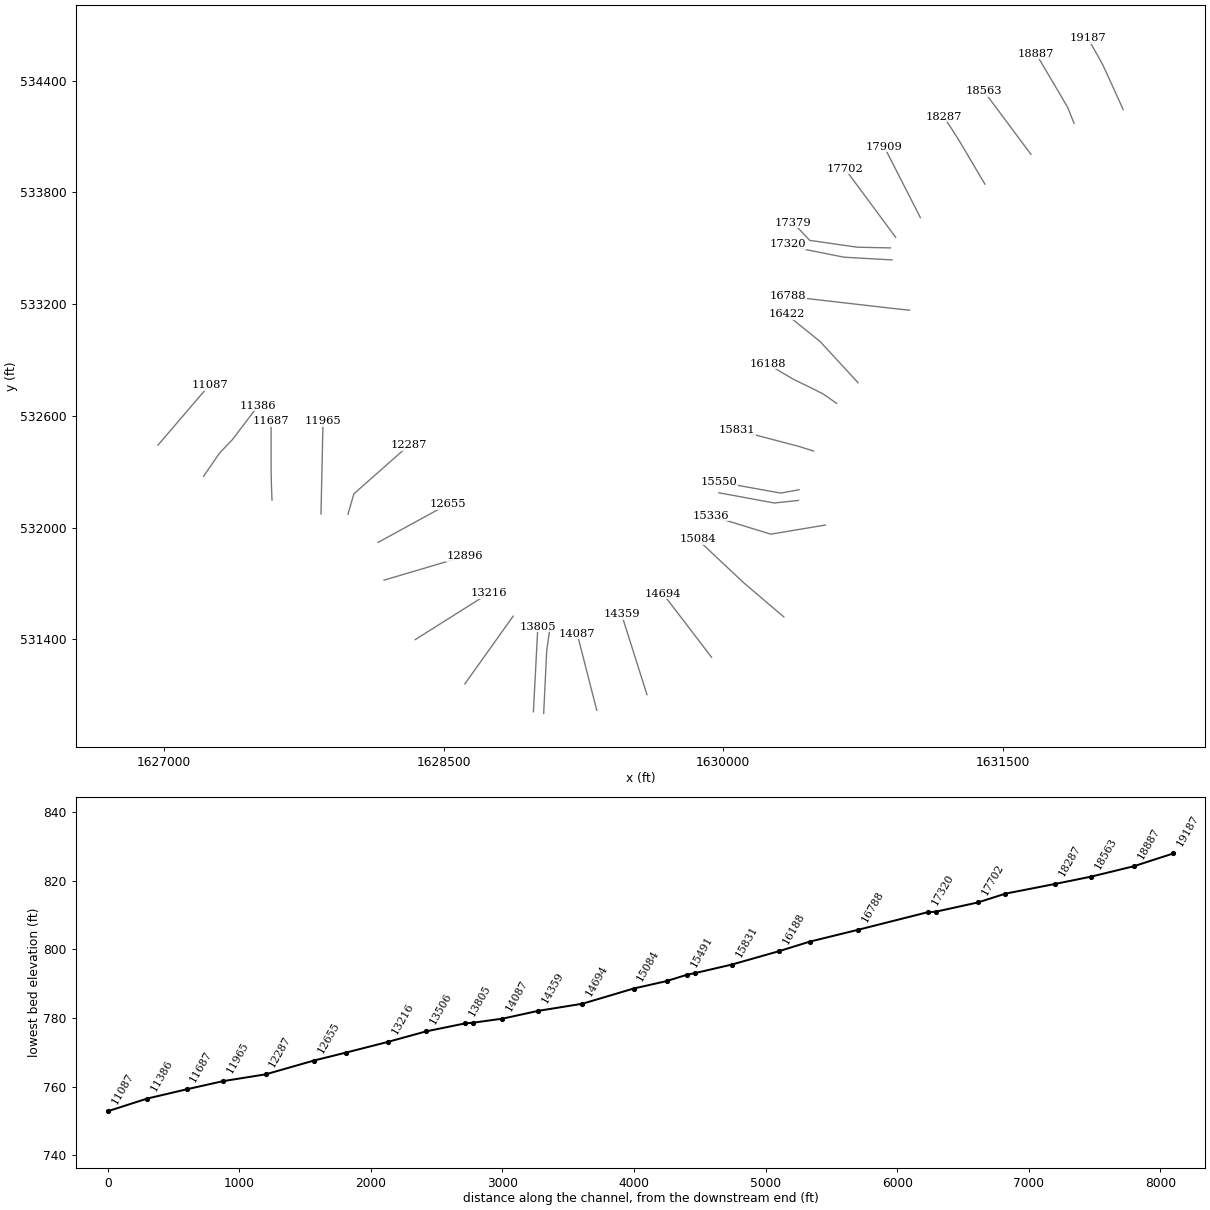
HEC-RAS study LtlGraveCk.prj: LtlGraveCk

--- LtlGraveCk.g01 (geometry) --- (continued)

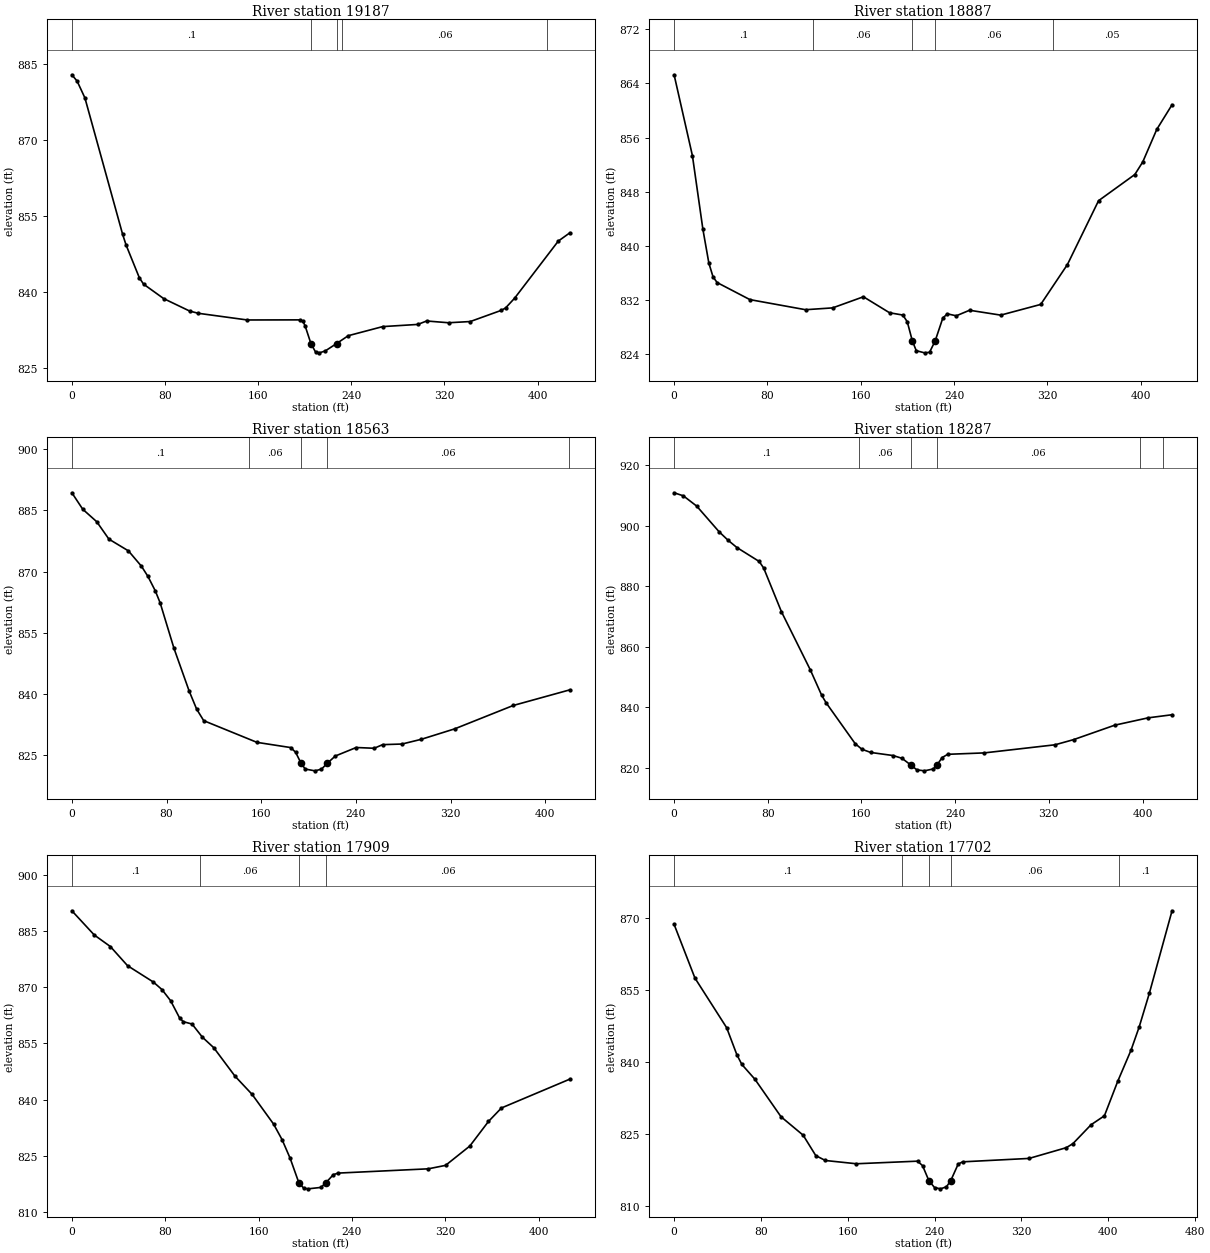
Type RM Length L Ch R = 1 ,19187   ,295.4,299.8,295.7
XS GIS Cut Line= 6
1632147.47080925534244.9905345891632111.37737751 534324.65212068
1632080.43911918534392.9370890861632038.81584284534483.915581673
1632002.27457733534550.048651502  1631957.867842 534627.93891567
#Sta/Elev= 30
       0  882.92     4.5  881.67    11.2  878.34    43.6  851.36    46.6  849.23
      58  842.75    61.6  841.51    78.9  838.65   101.2  836.19   108.6  835.75
   150.7  834.43   196.2  834.45   198.5  834.14   200.3  833.29  205.32829.7732
   209.3  828.09   212.6  827.93   217.6   828.3  227.41829.7715   237.4  831.32
     267  833.12   297.2  833.55   304.7  834.23   323.5  833.88   342.2  834.12
   368.7  836.32   372.5   836.8   380.3  838.74   417.8  850.03   427.7  851.66
#Mann= 5, -1 ,  0
       0     0.1       0  205.32   0.045       0  227.41     0.1       0
  232.42    0.06       0  408.03    0.05       0
Bank Sta=205.32,227.41
XS Rating Curve= 0 ,0
Exp/Cntr(USF)=0,0
Exp/Cntr=0.3,0.1

Type RM Length L Ch R = 1 ,18887   ,322.7,324,324.6
XS GIS Cut Line= 6
1631883.77743901534171.7072165911631850.44056343534254.699504673
1631813.11091368534319.7571173461631762.17597617534405.813375667
  1631723.974609534470.3552413431631679.33821534534545.604762763
#Sta/Elev= 30
       0  865.28    15.7  853.33    24.7  842.44    29.8  837.46    33.4  835.42
    36.9  834.59      65  832.07   112.7  830.58   135.9  830.85   162.3  832.49
   184.7  830.13   196.1  829.79   199.9   828.8  204.22825.9921   207.6  824.53
   214.7  824.21     219  824.29  223.86825.9889   230.4  829.36   234.3  829.97
   241.9  829.68   253.3   830.5     280  829.78   314.3  831.36   337.2  837.25
   363.9  846.68     395  850.55   401.8  852.41   413.8  857.21   426.9  860.85
#Mann= 5, -1 ,  0
       0     0.1       0  119.44    0.06       0  204.22   0.045       0
  223.86    0.06       0  324.44    0.05       0
Bank Sta=204.22,223.86
XS Rating Curve= 0 ,0
Exp/Cntr(USF)=0,0
Exp/Cntr=0.3,0.1

Type RM Length L Ch R = 1 ,18563   ,276.5,276,274.5
XS GIS Cut Line= 2
1631652.00645884534005.0073002091631400.96016318534342.749197334
#Sta/Elev= 30
       0  889.33     9.2  885.29      21  882.24    31.3  877.97    47.8  875.09
    58.8  871.33    64.3  868.82    70.5  865.29    74.6  862.35    86.3  851.19
    99.1  840.75   105.4  836.33   111.4  833.48   156.4  828.16     185  826.88
   189.1  825.72  193.67823.0432   197.2  821.62   205.4  821.18   210.9  821.59
  215.89823.0409   222.6  824.81   240.3   826.9   255.5  826.71   262.6   827.6
     279  827.75   295.3  828.91   323.5  831.47     373   837.2   420.8  841.03
#Mann= 5, -1 ,  0
       0     0.1       0     150    0.06       0  193.67   0.045       0
  215.89    0.06       0     420    0.05       0
Bank Sta=193.67,215.89
XS Rating Curve= 0 ,0
Exp/Cntr(USF)=0,0
Exp/Cntr=0.3,0.1

Type RM Length L Ch R = 1 ,18287   ,378.9,378.3,377.4
XS GIS Cut Line= 6
1631405.27216242533844.8459936681631360.75519109533920.180816755
1631322.59581859533984.7587715831631271.61494942534070.787470922
1631231.73510793534134.3263858411631183.17155676534207.258982763
#Sta/Elev= 30
       0  910.85     7.9  909.84    19.3  906.45    38.4  897.99      46   895.2
    53.6  892.78    72.7  888.16    76.5  885.99    91.7  871.54   116.3  852.39
     126     844   129.8  841.51   154.6  828.03   160.3  826.18   167.9  825.11
     187  824.09   194.6  823.18  202.07820.9758   207.3  819.37   213.7  819.04
   221.3  819.66  224.49820.9767   228.9  823.43   233.7   824.5   264.8  824.96
   325.3  827.64   341.1  829.34   376.3  834.12   404.8  836.54   425.2  837.56
#Mann= 6, -1 ,  0
       0     0.1       0   157.5    0.06       0  202.07   0.045       0
  224.49    0.06       0  397.53    0.05       0  417.53    0.06       0
Bank Sta=202.07,224.49
XS Rating Curve= 0 ,0
Exp/Cntr(USF)=0,0
Exp/Cntr=0.3,0.1

Type RM Length L Ch R = 1 ,17909   ,205.3,207.3,208.5
XS GIS Cut Line= 2
1631058.92073424533664.7644100221630864.92517941 534044.90326474
#Sta/Elev= 30
       0  890.37    19.2  883.91      33  880.83    47.7  875.73    69.8  871.37
    77.2  869.36    84.6   866.4    92.4  861.74    95.6  860.78     103  860.16
   111.9  856.64   121.6  853.85   139.8  846.26   154.5  841.39   172.9  833.47
   180.2   829.3   187.1  824.34  194.54817.8328   198.7  816.38   202.4   816.2
   213.5  816.58  217.73817.8353   224.1  819.98   228.2   820.4   305.5  821.54
   320.3  822.46   341.1  827.62   357.1  834.18   368.2  837.77   426.8  845.46
#Mann= 4, -1 ,  0
       0     0.1       0     110    0.06       0  194.54   0.045       0
  217.73    0.06       0
Bank Sta=194.54,217.73
XS Rating Curve= 0 ,0
Exp/Cntr(USF)=0,0
Exp/Cntr=0.3,0.1

Type RM Length L Ch R = 1 ,17702   ,314.5,322.5,333.1
XS GIS Cut Line= 2
1630926.23223104533559.1646664921630653.49315417533927.954423249
#Sta/Elev= 30
       0   868.7    19.2  857.52    48.4   847.2    57.8  841.58    62.4  839.55
    74.4  836.48    98.5  828.66   118.9  824.82   130.5  820.58   139.3  819.56
   167.9  818.88   224.3  819.42   228.9  818.48  234.68815.3728   239.9  813.93
   245.4  813.66   250.9  814.09  254.86815.3745   261.7  818.82   265.8  819.28
     327  819.99   361.3  822.23   367.4  823.07   384.1     827   396.4  828.86
   408.6     836   420.9  842.51   428.4  847.33   437.8  854.37   458.7  871.53
#Mann= 5, -1 ,  0
       0     0.1       0     210    0.06       0  234.68   0.045       0
  254.86    0.06       0     410     0.1       0
Bank Sta=234.68,254.86
XS Rating Curve= 0 ,0
Exp/Cntr(USF)=0,0
Exp/Cntr=0.3,0.1

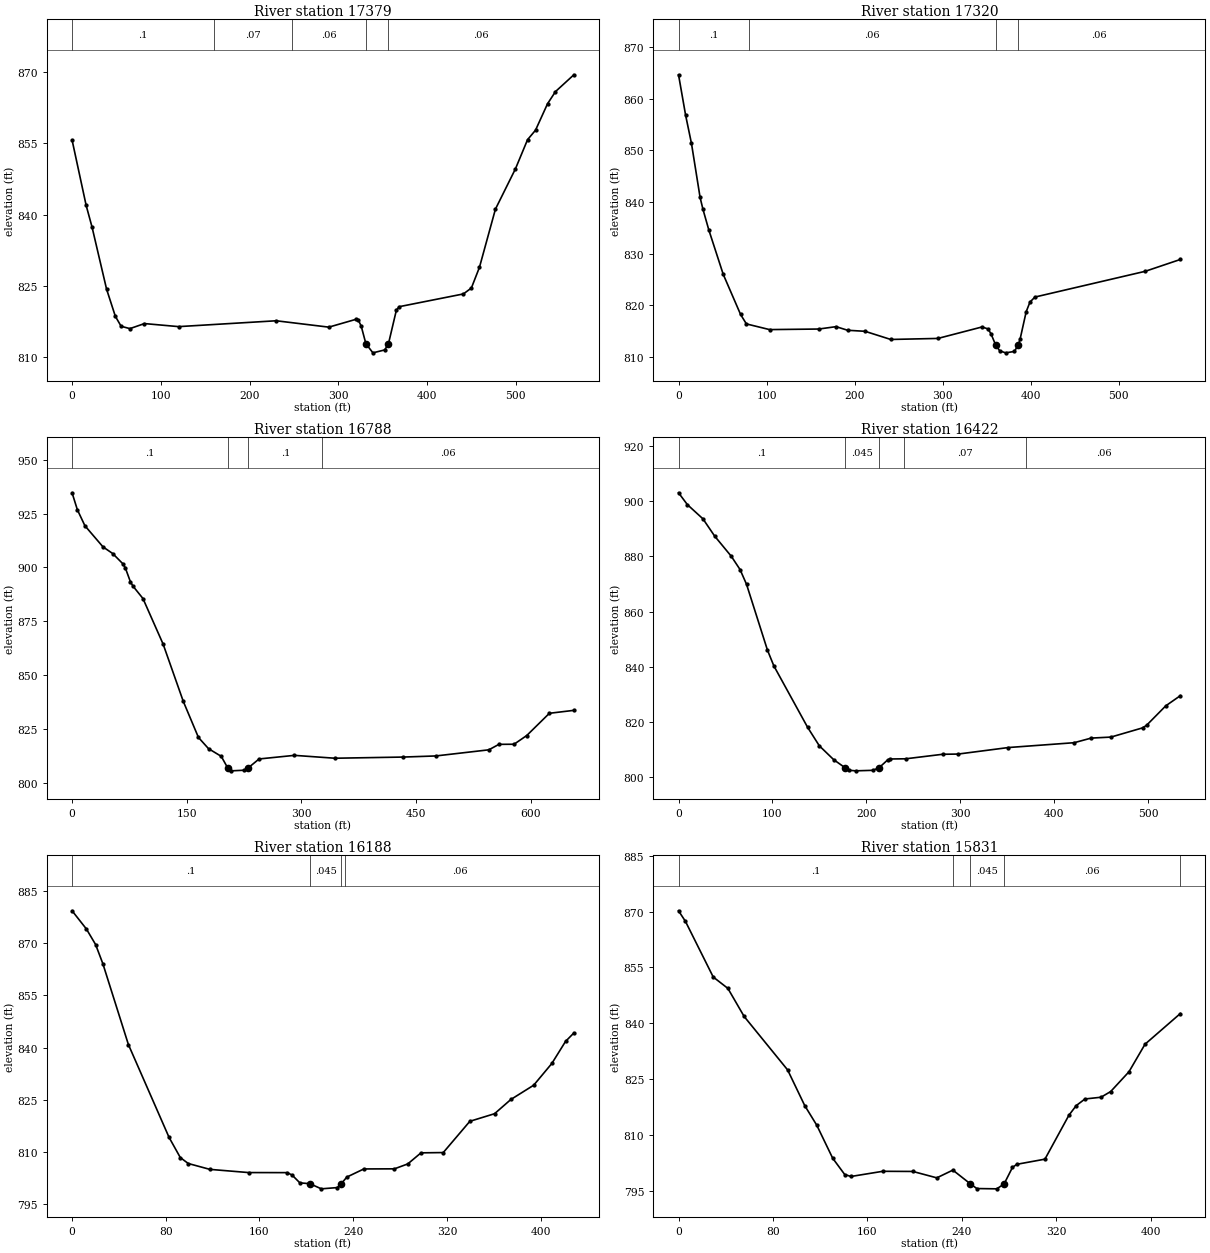
Type RM Length L Ch R = 1 ,17379   ,58.8,58.8,57.5
XS GIS Cut Line= 4
1630897.95232532533502.1954665621630720.09794206533505.977861341
1630464.87894219533542.5916988691630375.67481217533636.944506586
#Sta/Elev= 30
       0  855.67    15.9  841.91    22.5  837.38    38.9  824.32    48.8  818.61
    55.3  816.52    65.2  816.03    81.6  817.09   120.1  816.45   230.1  817.68
   289.4  816.34   319.9  817.98   322.6  817.85   325.9  816.56  331.17812.8641
   339.1  810.94   352.4  811.55  356.65812.8666   365.6  819.95     369  820.65
   441.1  823.32   450.1  824.57   459.2  828.92   477.2  841.14   499.8  849.63
   513.4  855.74   522.4  857.74   535.9  863.28   544.9  865.85   565.6  869.38
#Mann= 5, -1 ,  0
       0     0.1       0     160    0.07       0  247.89    0.06       0
  331.17   0.045       0  356.65    0.06       0
Bank Sta=331.17,356.65
XS Rating Curve= 0 ,0
Exp/Cntr(USF)=0,0
Exp/Cntr=0.3,0.1

Type RM Length L Ch R = 1 ,17320   ,511.4,532,509.1
XS GIS Cut Line= 4
1630906.51483866533437.5524083791630648.58389423533452.354513411
1630443.32091417533493.3762350411630345.13776098533522.599380757
#Sta/Elev= 30
       0  864.66     8.1  856.78    14.7  851.36    24.5   840.9    27.8  838.58
    34.4  834.62    50.8  826.01    70.5  818.25    77.1  816.42   103.4  815.32
   159.3  815.43     179  815.89   192.1  815.19   211.9  814.99   241.1  813.41
   294.7  813.61   344.8  815.83   351.5  815.46   354.9  814.55  360.12812.4028
   364.9  811.21   371.6  810.82   381.6  811.09  386.09812.4048   388.2  813.58
     395   818.8   399.3  820.65   404.9  821.62   530.3  826.61   570.1   828.9
#Mann= 4, -1 ,  0
       0     0.1       0      80    0.06       0  360.12   0.045       0
  386.09    0.06       0
Bank Sta=360.12,386.09
XS Rating Curve= 0 ,0
Exp/Cntr(USF)=0,0
Exp/Cntr=0.3,0.1

Type RM Length L Ch R = 1 ,16788   ,365.1,366.5,344.2
XS GIS Cut Line= 3
1631000.42126609533167.594395429  1630913.413238533176.859140679
1630348.34207431533241.836132369
#Sta/Elev= 30
       0  934.66     6.9  926.81    16.8  919.36    40.5  909.54    53.1  906.49
    66.3  901.77    69.6  899.87    76.2  893.48    79.5  891.43    92.7  885.61
   119.1  864.45   145.5  837.86   165.3  821.15   178.5  815.95   195.1   812.4
  203.44807.0978   208.3  805.67   224.8  805.95  230.57807.0963   244.6  811.18
   290.8  812.85   343.7  811.52   432.8  812.06   475.8  812.58   545.1  815.42
   558.3  817.96   578.1  818.01   594.7  822.06   624.3  832.37   656.3  833.73
#Mann= 4, -1 ,  0
       0     0.1       0  203.44   0.045       0  230.57     0.1       0
   327.5    0.06       0
Bank Sta=203.44,230.57
XS Rating Curve= 0 ,0
Exp/Cntr(USF)=0,0
Exp/Cntr=0.3,0.1

Type RM Length L Ch R = 1 ,16422   ,227.7,233.7,237.2
XS GIS Cut Line= 3
1630724.36977254532777.993080806 1630520.8268763532999.134784968
1630338.97359445533146.156415457
#Sta/Elev= 30
       0  903.05     9.4  898.76      26   893.6    38.5  887.33    56.2  880.02
    65.5  875.22    72.4  869.88    94.7     846   101.5  840.29   137.4  818.05
   149.9  811.32   165.3  806.26  177.05803.4311   181.6  802.45   188.5  802.23
   207.1  802.42  213.82803.4307   222.6  806.16   225.7  806.53     242   806.6
   281.4  808.24   297.7  808.31   351.3  810.68   421.3  812.43   439.4   814.1
   460.5  814.47   494.2  817.81   498.5  818.76   518.9   825.8   534.4  829.48
#Mann= 5, -1 ,  0
       0     0.1       0  177.05   0.045       0  213.82    0.06       0
     240    0.07       0  370.56    0.06       0
Bank Sta=177.05,213.82
XS Rating Curve= 0 ,0
Exp/Cntr(USF)=0,0
Exp/Cntr=0.3,0.1

Type RM Length L Ch R = 1 ,16188   ,354.5,357.7,359.7
XS GIS Cut Line= 6
1630609.80984259532666.8463811731630537.54456717532717.265899763
 1630470.5853835532751.2084171771630380.55866067532794.850390255
1630314.77926467532832.894933596  1630239.528759532880.737685665
#Sta/Elev= 30
       0  879.25    12.2  874.04    20.1  869.56    26.3  864.05    48.1  840.85
    82.8  814.22    92.4  808.43    99.2  806.72   117.6  805.04   150.7  804.12
   183.6   804.1   187.8  803.42   194.5  801.16  203.05800.9296   212.8  799.45
   226.4  799.81  229.84800.9301   234.6  802.83   249.1  805.16   275.2  805.19
   286.6   806.6   297.9  809.78   316.9  809.86   339.6  818.83   360.7  821.01
   374.6  825.09   394.1  829.19   409.6  835.43   421.3  841.76   428.4  844.18
#Mann= 4, -1 ,  0
       0     0.1       0  203.05   0.045       0  229.84     0.1       0
  233.19    0.06       0
Bank Sta=203.05,229.84
XS Rating Curve= 0 ,0
Exp/Cntr(USF)=0,0
Exp/Cntr=0.3,0.1

Type RM Length L Ch R = 1 ,15831   ,278.5,280.4,281
XS GIS Cut Line= 6
1630485.57968596532411.0940607731630401.99848829532437.323667103
1630329.44581188532456.3269099391630232.70880063 532481.66380153
 1630160.1564523532500.6677005241630075.51193655532522.837931776
#Sta/Elev= 30
       0  870.23     5.9  867.36    29.4  852.44    41.8  849.39    55.6  841.84
    92.4   827.5   106.9  817.92   117.1  812.65   130.6  803.78   140.8   799.4
   146.1  798.88     173  800.27   198.5  800.23   218.8  798.51   232.4  800.59
  247.31796.8793   252.7  795.64   269.6  795.56  275.81796.8788   282.9  801.32
   286.6  802.15   310.4  803.53   330.7  815.32   336.9  817.91   344.3  819.69
   357.9  820.16   366.1  821.69   381.6     827   395.2   834.4   425.1  842.63
#Mann= 5, -1 ,  0
       0     0.1       0   232.6    0.06       0  247.31   0.045       0
  275.81    0.06       0   425.1     0.1       0
Bank Sta=247.31,275.81
XS Rating Curve= 0 ,0
Exp/Cntr(USF)=0,0
Exp/Cntr=0.3,0.1

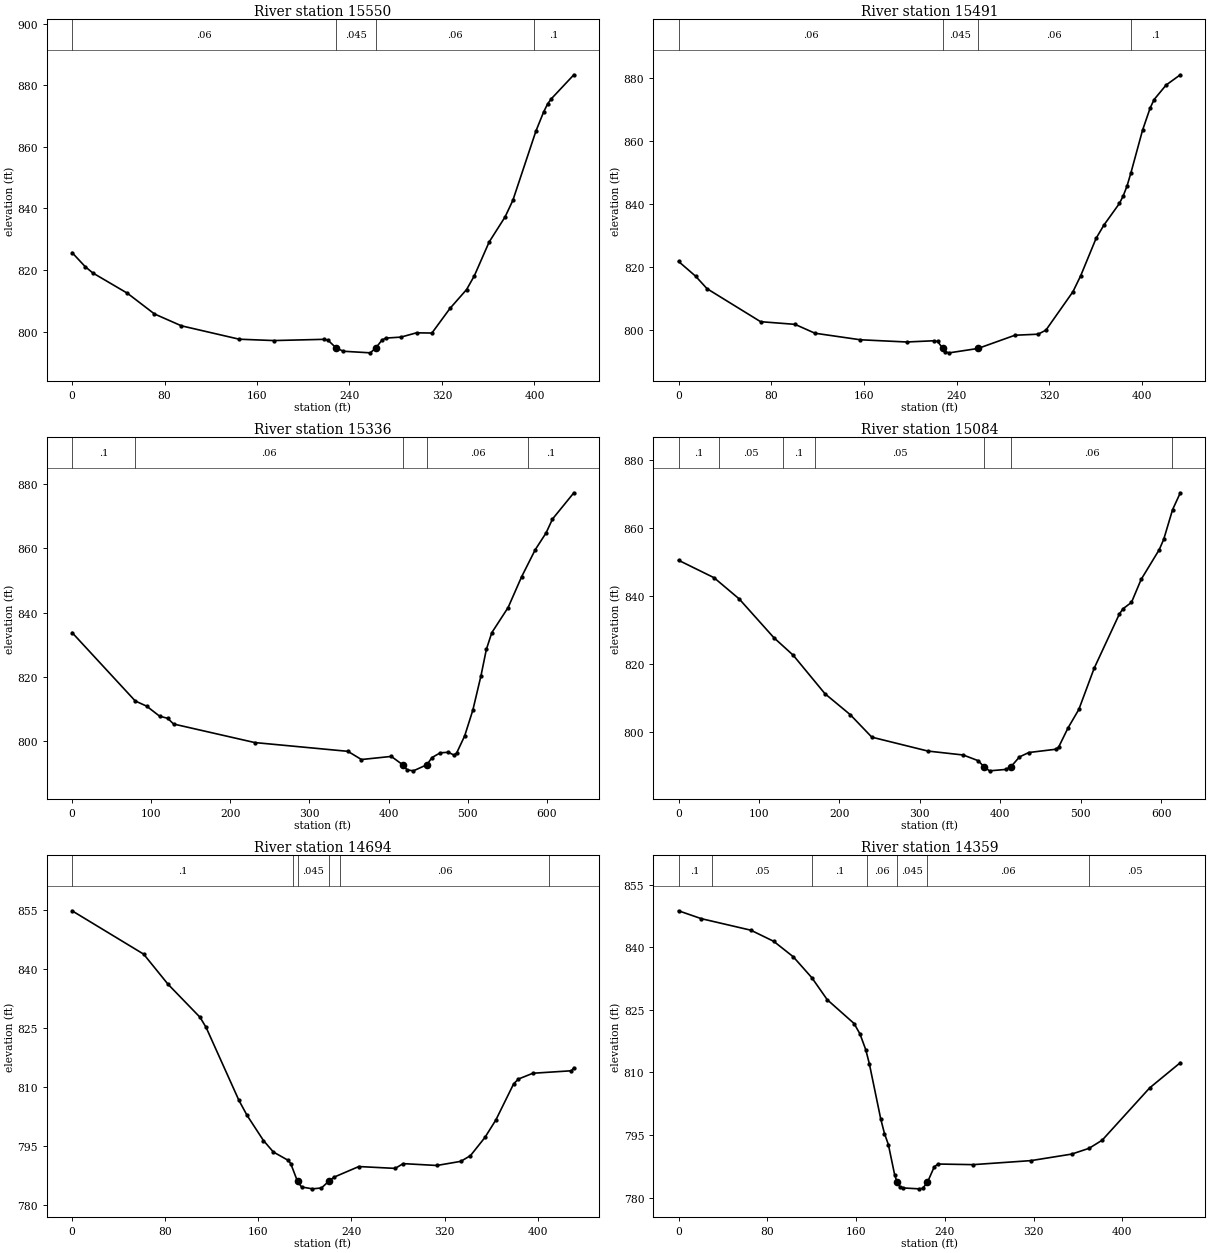
Type RM Length L Ch R = 1 ,15550   ,58.4,59.6,58.8
XS GIS Cut Line= 3
1630407.52526118532203.1698290881630309.23833876532185.248129991
1629980.32361426532244.267176391
#Sta/Elev= 30
       0  825.65    11.3   821.1    17.9  819.04    47.9  812.43    71.3   805.7
    94.6  801.85   144.6   797.5   174.6  797.06     218  797.46   221.3   797.2
  228.48794.6663   234.6  793.59     258  793.07  262.76794.6638     268  797.16
   271.3  797.86   284.5  798.18     298  799.58   311.3   799.5   326.9  807.49
   341.3  813.64     348   818.1   360.8  829.08   374.6  837.24   381.3   842.6
   401.3  865.16   407.9  871.29   411.3  873.89   414.5  875.59   434.1  883.43
#Mann= 4, -1 ,  0
       0    0.06       0  228.48   0.045       0  262.76    0.06       0
  399.91     0.1       0
Bank Sta=228.48,262.76
XS Rating Curve= 0 ,0
Exp/Cntr(USF)=0,0
Exp/Cntr=0.3,0.1

Type RM Length L Ch R = 1 ,15491   ,155.7,154.6,152.2
XS GIS Cut Line= 3
1630404.47279104532145.7464441411630275.16742495532131.906119211
1629977.27114412532186.843791444
#Sta/Elev= 30
       0  821.69    14.7     817    24.6  813.01    70.8  802.52   100.5  801.67
   117.7  798.85   156.8  796.77   196.9  796.06   220.2  796.45   223.6  796.22
  228.08 793.998   230.2  792.89   233.6  792.61  258.37 793.998   290.3  798.21
   310.3  798.54     317  799.82   340.3  812.03     347  817.11   360.3  829.02
     367  833.21   380.4  840.11   383.7  842.51     387  845.66   390.4  849.91
   400.4  863.42     407  870.52   410.4  873.18   420.7  877.78     433  881.05
#Mann= 4, -1 ,  0
       0    0.06       0  228.08   0.045       0  258.37    0.06       0
  390.04     0.1       0
Bank Sta=228.08,258.37
XS Rating Curve= 0 ,0
Exp/Cntr(USF)=0,0
Exp/Cntr=0.3,0.1

Type RM Length L Ch R = 1 ,15336   ,255.5,251.7,239.7
XS GIS Cut Line= 6
1630548.37214686532013.4529106631630255.72760463531964.538222611
1630184.04402097531986.5946089471630088.46612813532016.003342777
1630016.78254447532038.059729114 1629933.1521343532063.792617276
#Sta/Elev= 30
       0  833.79    79.9  812.49    94.2   810.9   110.8  807.74   120.8  807.12
   128.3  805.33   230.9  799.56   348.6  796.83   365.7  794.28   403.5  795.25
  417.91792.6426   423.5  791.06   431.4  790.76  448.33792.6418   454.9   794.9
   465.5  796.38   475.6  796.53   482.4   795.7   485.9  796.22   496.2  801.63
   506.5  809.63   516.8  820.34   523.6  828.54   530.5  833.76   551.1  841.58
   568.2  851.17   585.4  859.58   599.1   864.8   607.2  869.12   634.2  877.29
#Mann= 5, -1 ,  0
       0     0.1       0      80    0.06       0  417.91   0.045       0
  448.33    0.06       0   576.7     0.1       0
Bank Sta=417.91,448.33
XS Rating Curve= 0 ,0
Exp/Cntr(USF)=0,0
Exp/Cntr=0.3,0.1

Type RM Length L Ch R = 1 ,15084   ,390.6,389.9,387
XS GIS Cut Line= 3
1630325.91513375531519.9220178261630109.96075992531703.927920055
1629862.30898073531936.679294731
#Sta/Elev= 30
       0  850.55    44.1  845.42    75.4  839.17   118.5  827.76   142.5  822.61
     182  811.27   213.4  805.11   240.2  798.49   309.9   794.4   353.8  793.24
   372.6  791.55  379.47789.7838   386.5  788.58   406.5  788.99  413.07 789.784
   423.7  792.68   435.3  793.97   468.8  794.93   472.4  795.58     484  801.19
   497.5  806.66   516.5  818.76   547.9  834.76   552.4  836.28   562.9  838.15
   574.9  844.91   597.4  853.67   602.9  856.67     614  865.46   623.6  870.41
#Mann= 7, -1 ,  0
       0     0.1       0      50    0.05       0     130     0.1       0
     170    0.05       0  379.47   0.045       0  413.07    0.06       0
  613.72     0.1       0
Bank Sta=379.47,413.07
XS Rating Curve= 0 ,0
Exp/Cntr(USF)=0,0
Exp/Cntr=0.3,0.1

Type RM Length L Ch R = 1 ,14694   ,339.5,335.5,330.2
XS GIS Cut Line= 2
1629938.23489202531302.7934547061629676.69315052531645.313467353
#Sta/Elev= 30
       0  854.73    61.5  843.72    82.4  836.09   109.9   827.7   115.1  825.14
   143.3  806.62   150.3   802.8   164.4  796.41   172.9   793.5   185.6  791.39
   187.8  790.57  193.63786.0518   197.1  784.62   206.5  784.15   214.2  784.37
  220.42786.0494   225.2  787.14   246.3  789.81   277.5  789.34   284.4  790.55
   313.3  790.08   333.9  791.13   342.2  792.58   354.6  797.19     364  801.63
   379.3  810.81   383.4  812.02   395.8  813.49   428.9  814.12     431  814.86
#Mann= 6, -1 ,  0
       0     0.1       0     190    0.06       0  193.63   0.045       0
  220.42     0.1       0     230    0.06       0     410    0.05       0
Bank Sta=193.63,220.42
XS Rating Curve= 0 ,0
Exp/Cntr(USF)=0,0
Exp/Cntr=0.3,0.1

Type RM Length L Ch R = 1 ,14359   ,271.7,271.5,270.2
XS GIS Cut Line= 2
1629591.32959609531102.4938668461629454.89700822531533.632410115
#Sta/Elev= 30
       0  848.75    20.5  846.86    65.2  844.09    85.8  841.42   103.4  837.72
   120.2  832.68     134  827.43   158.2  821.72   163.5  819.22   168.7  815.45
   171.9  812.13   182.2  798.86   185.6  795.33   189.1  792.69   194.8   785.4
  197.05 783.646   199.4  782.62   202.7  782.29   216.6  782.08     220  782.18
  224.29783.6408   230.4  787.33   233.8  788.03   265.4  787.88   317.7  788.85
   354.3  790.41     370   791.8   381.8  793.75   424.6  806.29   452.2  812.33
#Mann= 7, -1 ,  0
       0     0.1       0      30    0.05       0     120     0.1       0
     170    0.06       0  197.05   0.045       0  224.29    0.06       0
     370    0.05       0
Bank Sta=197.05,224.29
XS Rating Curve= 0 ,0
Exp/Cntr(USF)=0,0
Exp/Cntr=0.3,0.1

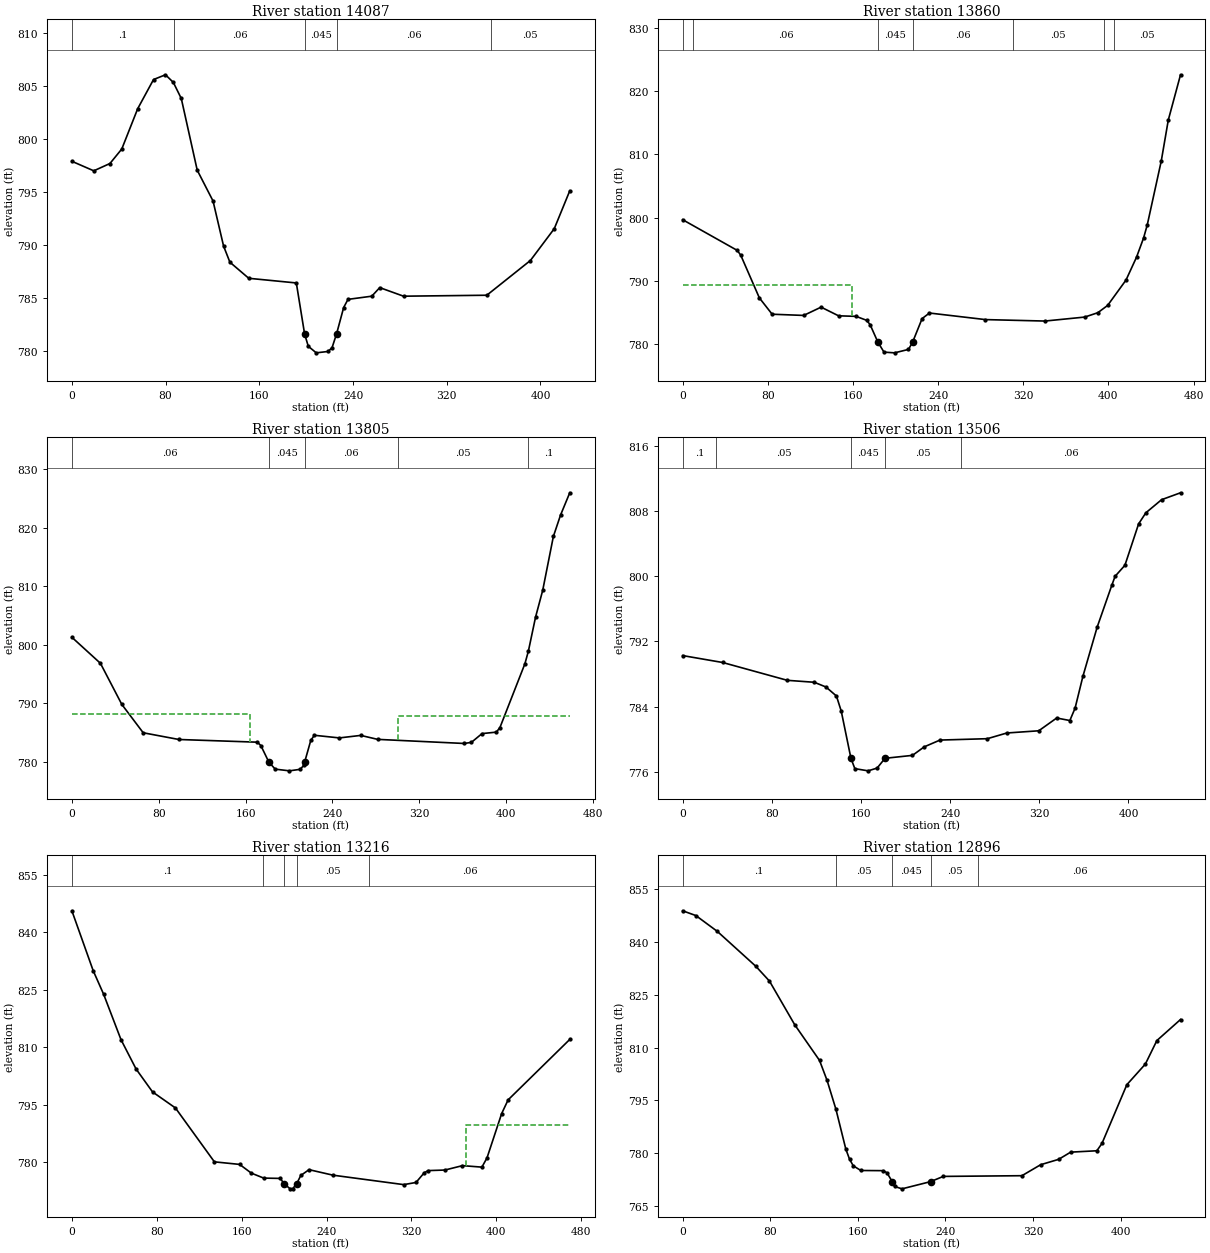
Type RM Length L Ch R = 1 ,14087   ,231.6,227.1,222.7
XS GIS Cut Line= 6
1629321.88000375531018.3769090921629300.17105767531103.140847176
1629281.56348334531175.7962136721629256.75382167531272.669707596
1629238.14657542531345.3247460131629216.43631701531430.088356003
#Sta/Elev= 30
       0   797.9    18.7     797    32.5  797.69    42.6  799.06    56.2  802.87
    69.7  805.62    79.9  806.07    86.6  805.35    93.4  803.83     107  797.06
   120.5  794.15   129.5  789.89   134.9  788.37     151  786.85   191.6  786.41
  198.65781.5958   201.8  780.43   208.6  779.81   218.7  779.94   222.1   780.3
  225.93781.5955     232  784.09   235.7  784.86     256  785.16   262.8  785.97
   283.1  785.16   354.2  785.25   391.4  788.53   411.8  791.54     425  795.11
#Mann= 5, -1 ,  0
       0     0.1       0    87.5    0.06       0  198.65   0.045       0
  225.93    0.06       0   357.5    0.05       0
Bank Sta=198.65,225.93
XS Rating Curve= 0 ,0
Exp/Cntr(USF)=0,0
Exp/Cntr=0.3,0.1

Type RM Length L Ch R = 1 ,13860   ,55,55.2,54.9
XS GIS Cut Line= 3
1629036.94651112531001.8768830061629052.98484955531336.978060479
1629071.47201247531468.010529553
#Sta/Elev= 30
       0  799.68    51.3  794.82    54.6  794.06    72.1   787.3    84.1  784.72
   113.7  784.53   130.1  785.84   146.5  784.47     163  784.38   172.8  783.76
   176.1  783.09  183.44 780.306   189.2  778.72   199.1  778.61   212.2  779.15
  216.09780.3055     225  784.03   231.9  784.91   284.5  783.87   340.4  783.64
   377.8  784.27   390.1  784.96   399.3  786.11   416.6  790.13   426.5  793.76
   433.1  796.79   436.5  798.82   449.7  808.96   456.3  815.44   467.8  822.61
#Mann= 7, -1 ,  0
       0     0.1       0      10    0.06       0  183.44   0.045       0
  216.09    0.06       0     310    0.05       0  395.48     0.1       0
  405.48    0.05       0
#XS Ineff= 2 , 0
          159.57  789.27
Permanent Ineff=
       F       F
Bank Sta=183.44,216.09
XS Rating Curve= 0 ,0
Exp/Cntr(USF)=0,0
Exp/Cntr=0.3,0.1

Type RM Length L Ch R = 1 ,13805   ,307,298.9,289.4
XS GIS Cut Line= 2
1628981.72698069531010.427410477 1629005.6409092531468.398308688
#Sta/Elev= 30
       0  801.28    26.3  796.83      46   789.8    65.7  784.95    98.6   783.8
   170.9  783.34   174.1  782.75  181.44779.9348   187.3  778.73   200.4  778.44
   210.3   778.7   213.6  779.38   214.4779.9332   220.1  783.67   223.4  784.52
   246.4  784.07   266.1   784.5   281.7  783.82   361.4  783.12     368  783.31
   377.8  784.81     391  785.06   394.3  785.85   417.3  796.76   420.5  798.92
   427.1  804.73   433.7  809.32   443.5  818.52   450.1  822.17   458.6  825.99
#Mann= 5, -1 ,  0
       0    0.06       0  181.44   0.045       0   214.4    0.06       0
     300    0.05       0     420     0.1       0
#XS Ineff= 2 , 0
          164.26  788.18  300.36          787.85
Permanent Ineff=
       F       F
Bank Sta=181.44,214.4
XS Rating Curve= 0 ,0
Exp/Cntr(USF)=0,0
Exp/Cntr=0.3,0.1

Type RM Length L Ch R = 1 ,13506   ,294.4,290.4,285.2
XS GIS Cut Line= 2
1628613.84482311531160.3124390071628873.01535448531524.142360598
#Sta/Elev= 30
       0  790.26    35.9  789.41    93.9  787.22   118.1  786.98   128.6   786.4
     138  785.29   142.3  783.44     151  777.64   154.5  776.37   166.4   776.1
   174.5  776.44  181.56  777.64   206.2     778   216.8  779.05   230.9  779.88
   273.4  780.05   290.9  780.75   319.5  781.02   335.6  782.59   347.4  782.28
   352.1   783.8   359.1   787.7   371.9  793.75     385  798.88     388     800
   396.8  801.35   409.1  806.44   415.6   807.8   429.7  809.41   446.7  810.26
#Mann= 5, -1 ,  0
       0     0.1       0      30    0.05       0     151   0.045       0
  181.56    0.05       0     250    0.06       0
Bank Sta=151,181.56
XS Rating Curve= 0 ,0
Exp/Cntr(USF)=0,0
Exp/Cntr=0.3,0.1

Type RM Length L Ch R = 1 ,13216   ,321.1,319.7,310.3
XS GIS Cut Line= 2
1628347.26129679531398.0237179621628744.06166443531648.375886743
#Sta/Elev= 30
       0  845.54    20.1  829.91    29.9  823.79    46.3  811.93    60.5  804.28
      76  798.31    97.6  794.12   134.3  780.07   158.1   779.4   169.1  777.13
   180.8  775.83   196.3  775.75   200.2  774.33   205.7  773.03   208.2   773.1
   211.8  774.32   215.7  776.51   223.5  778.03   246.1  776.59   312.7  774.13
   324.3  774.69   332.1  777.24   335.9  777.79   351.5  777.93   368.1  779.08
   386.4  778.69   391.2  781.09     405  792.64   411.1  796.23   469.2  811.99
#Mann= 5, -1 ,  0
       0     0.1       0     180    0.05       0   200.2   0.045       0
   211.8    0.05       0     280    0.06       0
#XS Ineff= 2 , 0
                          371.27          789.59
Permanent Ineff=
       F       F
Bank Sta=200.2,211.8
XS Rating Curve= 0 ,0
Exp/Cntr(USF)=0,0
Exp/Cntr=0.3,0.1

Type RM Length L Ch R = 1 ,12896   ,238.7,240.9,244.5
XS GIS Cut Line= 2
1628180.11961084531717.5550630931628615.98124178531846.580900765
#Sta/Elev= 30
       0  848.86    12.1   847.5    31.7     843    66.9  833.08    79.3  828.89
   102.4  816.47     125  806.37   131.9  800.68     140  792.47     149  781.19
   152.4  778.32   155.8  776.45   162.7  775.12   183.2  775.07   186.6  774.46
  191.37771.9573   193.5  770.59   200.3  769.91  226.39771.9573     238  773.44
   309.8  773.64   326.9  776.76   343.3  778.28   354.3  780.33   378.2  780.72
   382.9  782.81   405.6  799.48   422.5  805.34     433  812.01   454.6  817.99
#Mann= 5, -1 ,  0
       0     0.1       0     140    0.05       0  191.37   0.045       0
  226.39    0.05       0     270    0.06       0
Bank Sta=191.37,226.39
XS Rating Curve= 0 ,0
Exp/Cntr(USF)=0,0
Exp/Cntr=0.3,0.1

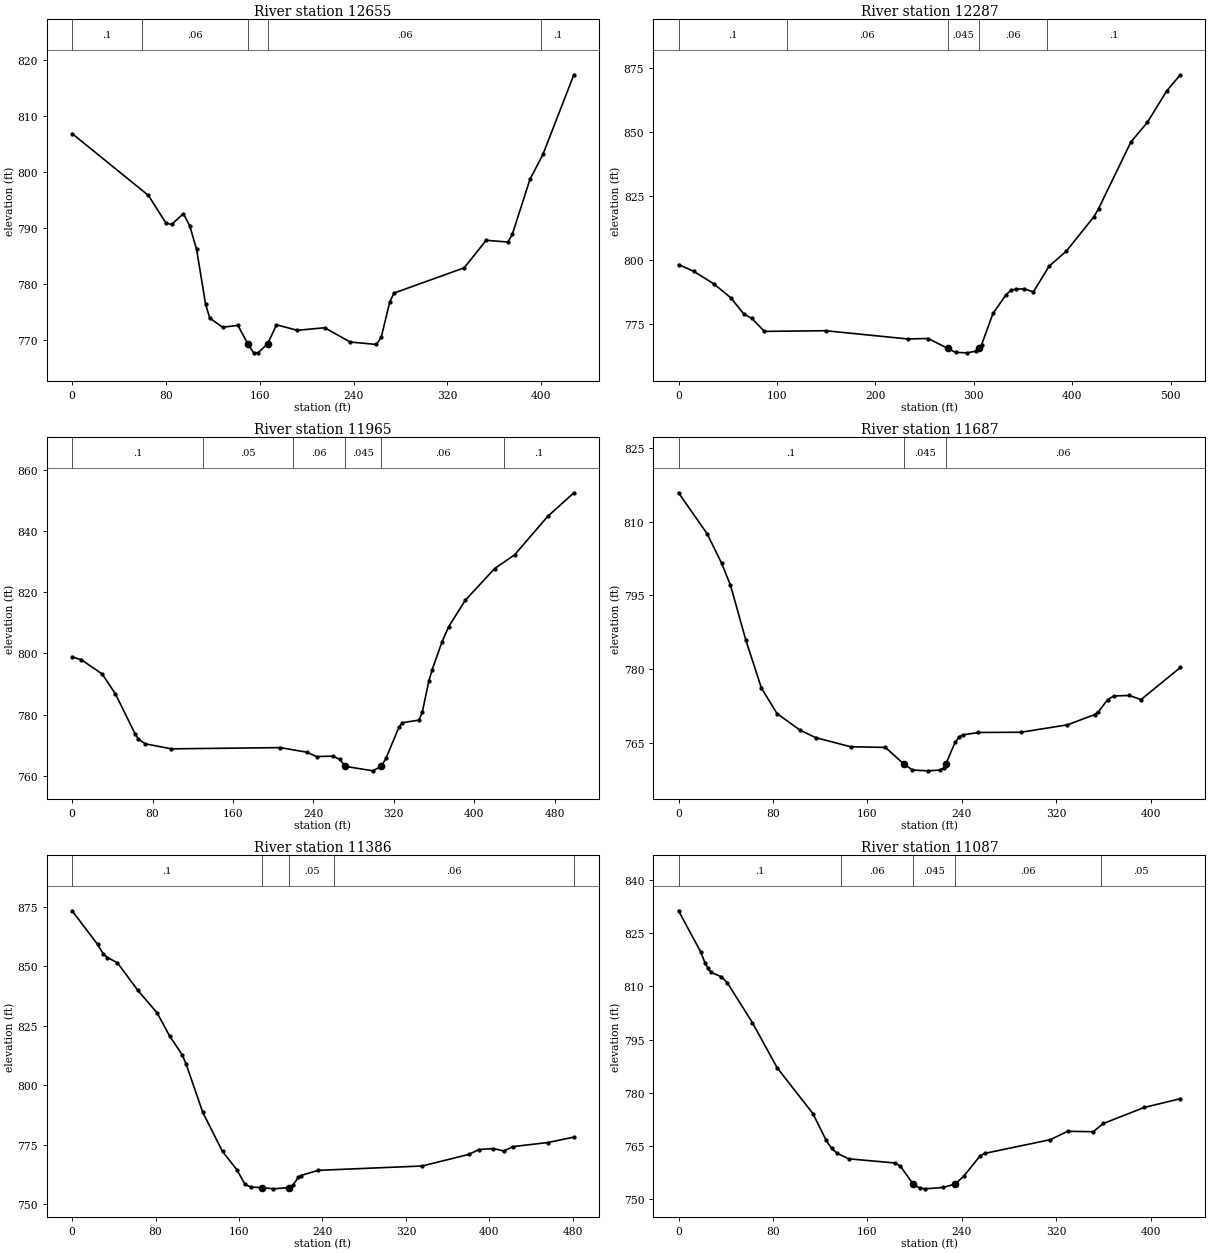
Type RM Length L Ch R = 1 ,12655   ,359.3,368,367.3
XS GIS Cut Line= 2
1628147.80605586531920.2193252041628523.11829737532125.655594129
#Sta/Elev= 30
       0  806.85    65.1  795.78      80  790.85    84.8  790.59      95  792.51
   100.4  790.29   106.2  786.12   113.8  776.38   117.4  773.84   128.3   772.2
   141.4  772.53  149.73769.2822   154.8  767.64   158.6  767.62  166.91  769.28
   174.3  772.63   192.2  771.65   215.4  772.11   237.1  769.56   259.6  769.12
   263.7  770.45   270.9  776.73   274.5  778.31   334.4  782.83   353.1  787.75
   371.8  787.44   375.5  788.89   390.5  798.67   401.5   803.1   427.9  817.36
#Mann= 5, -1 ,  0
       0     0.1       0      60    0.06       0  149.73   0.045       0
  166.91    0.06       0     400     0.1       0
Bank Sta=149.73,166.91
XS Rating Curve= 0 ,0
Exp/Cntr(USF)=0,0
Exp/Cntr=0.3,0.1

Type RM Length L Ch R = 1 ,12287   ,302.7,322.7,329.2
XS GIS Cut Line= 3
1627986.54701408532071.6702876351628017.93522478532181.177762942
1628314.68934242532443.433114661
#Sta/Elev= 30
       0  798.17    15.5  795.49      36  790.55    53.3  785.07    66.5  778.69
    74.5  777.09    87.2  771.99   149.4  772.25   232.8  769.03   253.7   769.2
  273.46 765.332   281.6  763.75   293.1  763.59   302.5  764.27  305.63765.3308
   307.9  766.71   319.6  779.09   332.7  786.26   337.6  788.03   342.6  788.55
   351.3  788.61   360.6  787.46   376.5  797.48   394.1  803.42   421.9  816.78
   426.8  820.02   459.7  846.15   476.4  853.82   496.2  866.21   509.9  872.45
#Mann= 5, -1 ,  0
       0     0.1       0     110    0.06       0  273.46   0.045       0
  305.63    0.06       0  373.92     0.1       0
Bank Sta=273.46,305.63
XS Rating Curve= 0 ,0
Exp/Cntr(USF)=0,0
Exp/Cntr=0.3,0.1

Type RM Length L Ch R = 1 ,11965   ,274.4,277.2,275.2
XS GIS Cut Line= 2
1627841.53453867532073.0593637721627852.52864248532571.955584398
#Sta/Elev= 30
       0  798.89     9.2  797.93    29.9   793.3      43  786.83    62.7  773.71
      66  772.01    72.6  770.46    98.8  768.81   207.1  769.21   233.4  767.71
   243.2  766.28   259.6  766.44   266.2  765.34  271.58763.0974     299  761.62
  307.61763.0955   312.1   765.7   325.2     776   328.5  777.35   344.9   778.2
   348.2  780.71   354.8  790.97   358.1   794.7   367.9  803.79   374.5  808.75
   390.9  817.32   420.2  827.74   440.1  832.24   472.9  844.77     499  852.52
#Mann= 6, -1 ,  0
       0     0.1       0     130    0.05       0     220    0.06       0
  271.58   0.045       0  307.61    0.06       0     430     0.1       0
Bank Sta=271.58,307.61
XS Rating Curve= 0 ,0
Exp/Cntr(USF)=0,0
Exp/Cntr=0.3,0.1

Type RM Length L Ch R = 1 ,11687   ,306.3,301,286.2
XS GIS Cut Line= 6
  1627578.616758532147.596763507 1627575.2683395532235.096588507
1627573.72798826532310.0967665911627573.72798826532410.096566588
1627573.72798826532485.0967446711627573.72798826532572.596569672
#Sta/Elev= 30
       0  815.87    24.3  807.49    36.4  801.56      44  797.04    57.1   785.8
    70.2  776.11    83.4  770.91   103.1   767.5   116.2  766.01   145.7  764.15
   175.3  764.01  190.99760.5919   198.2   759.4   211.3  759.24   221.2   759.4
   224.5  759.79  226.35760.5936   234.3  765.03   237.6  766.13   240.9  766.56
     254  767.05   290.1   767.1   329.5  768.61   352.4  770.69   355.7  771.26
   363.5  773.74   368.8  774.49   381.9  774.59   391.8  773.75   425.1  780.29
#Mann= 3, -1 ,  0
       0     0.1       0  190.99   0.045       0  226.35    0.06       0
Bank Sta=190.99,226.35
XS Rating Curve= 0 ,0
Exp/Cntr(USF)=0,0
Exp/Cntr=0.3,0.1

Type RM Length L Ch R = 1 ,11386   ,288,299,289.2
XS GIS Cut Line= 4
 1627211.2190487532275.1863143671627296.90603533532400.067715257
1627366.33798309532472.7673730111627504.65681219532655.196796728
#Sta/Elev= 30
       0  873.37    24.5  859.22    29.9  855.28    33.8  853.72    43.4  851.55
      63  839.95    81.6  830.42    93.5  820.75   105.5   812.9   109.4  808.84
   125.3  788.63   144.2  772.22     158  764.52   165.8  758.37   171.6  757.25
  181.66  757.08     193  756.53  208.09  757.08     212  758.33   216.8   761.3
   219.2  762.12   235.8   764.3   335.5  766.13   380.5  771.03   389.8  773.03
   403.9  773.47   413.7  772.44   422.6  774.27   456.1     776   480.9  778.26
#Mann= 5, -1 ,  0
       0     0.1       0  181.66   0.045       0  208.09    0.05       0
  251.45    0.06       0  480.92    0.05       0
Bank Sta=181.66,208.09
XS Rating Curve= 0 ,0
Exp/Cntr(USF)=0,0
Exp/Cntr=0.3,0.1

Type RM Length L Ch R = 1 ,11087   ,289.9,300,307.2
XS GIS Cut Line= 6
1626966.77250926532442.9997159991627023.64772359532509.494005591
1627072.39795418 532566.488642261627137.39815226532642.481928587
1627186.14838284532699.4768933361627243.02359718532765.970854834
#Sta/Elev= 30
       0  831.34    18.8  819.71    22.6   816.5      25  815.12    27.4  813.99
    36.1  812.74    41.3  811.03    62.5  799.79    83.6  786.99   113.8   774.1
     125  766.57   129.7  764.25   134.3  762.91     144  761.33   183.6  760.14
   187.9  759.24  198.74754.1784   204.1   753.1   208.9  752.85     224  753.24
   234.1754.1782   241.4  756.35   255.3  762.11   259.3  762.85   314.9  766.73
   329.6  769.09   351.2  768.98   359.9  771.31   394.4  775.82     425   778.3
#Mann= 5, -1 ,  0
       0     0.1       0   137.5    0.06       0  198.74   0.045       0
   234.1    0.06       0   357.5    0.05       0
Bank Sta=198.74,234.1
XS Rating Curve= 0 ,0
Exp/Cntr(USF)=0,0
Exp/Cntr=0.3,0.1