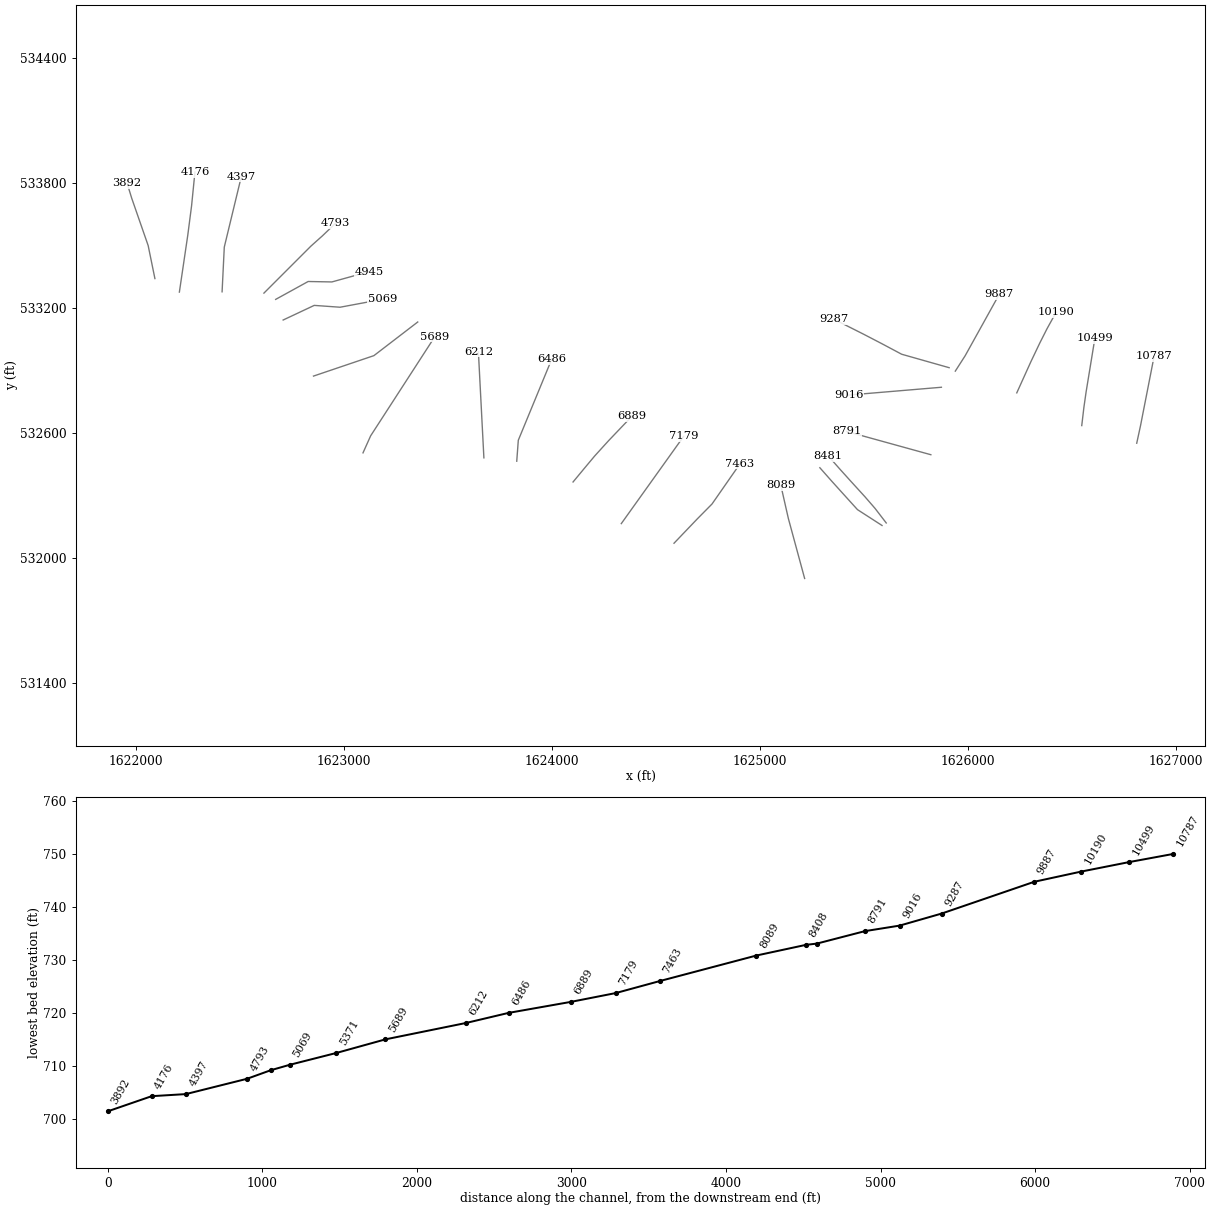
HEC-RAS study LtlGraveCk.prj: LtlGraveCk

--- LtlGraveCk.g01 (geometry) --- (continued)

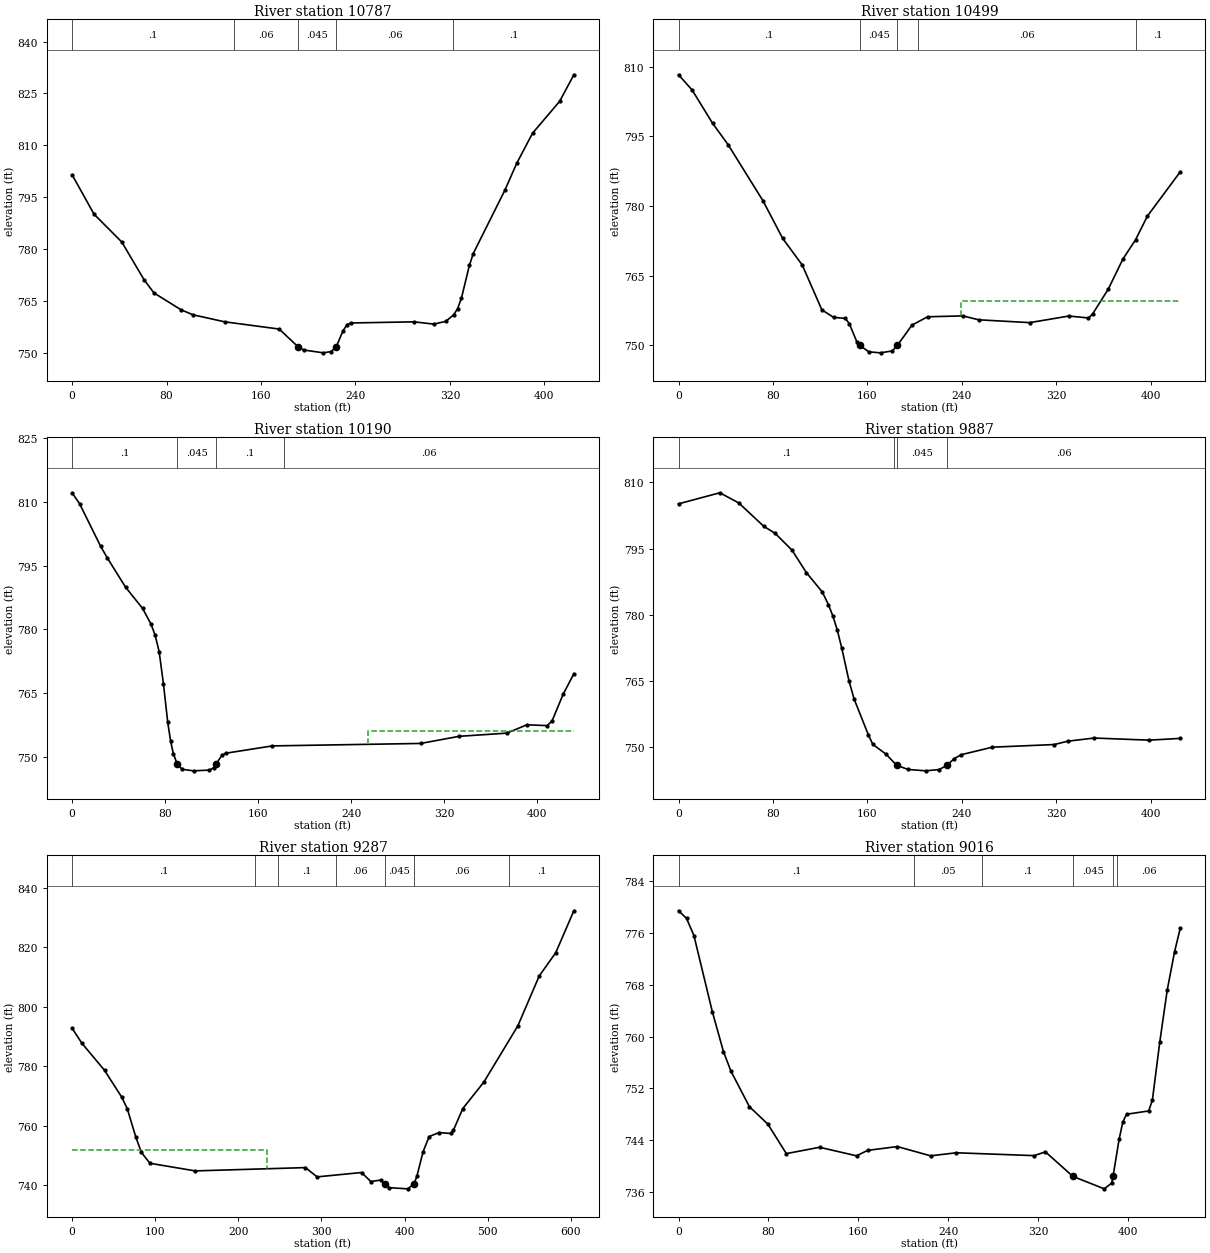
Type RM Length L Ch R = 1 ,10787   ,287.6,288.5,288.8
XS GIS Cut Line= 6
1626811.85484008532550.6336870941626830.35775584532636.177479252
1626844.76028609532709.7911771681626864.06241284532807.910731584
1626878.46133417532881.5060568451626895.26149742532967.373011082
#Sta/Elev= 30
       0   801.5    18.6  790.08    42.1  782.03    61.1  771.03    69.4  767.28
    92.4   762.4   102.5  760.96   129.2  758.94   175.4  756.84  191.22751.7747
   196.1  750.79   212.8  749.96   219.5  750.34  223.83751.7775   229.5  756.35
   232.9  758.11   236.2   758.6   289.7  758.93   306.4  758.27   316.4  759.06
   323.1  760.92   326.5   762.7   329.8  765.81   336.5  775.25   339.8   778.7
   366.6  797.03   376.6  804.79     390   813.5     413  822.75     425  830.41
#Mann= 5, -1 ,  0
       0     0.1       0  137.52    0.06       0  191.22   0.045       0
  223.83    0.06       0  322.53     0.1       0
Bank Sta=191.22,223.83
XS Rating Curve= 0 ,0
Exp/Cntr(USF)=0,0
Exp/Cntr=0.3,0.1

Type RM Length L Ch R = 1 ,10499   ,312.7,309,304
XS GIS Cut Line= 6
1626547.54616403532635.3870957881626557.79450312532722.375110784
1626568.40832704532796.6361171251626584.58644428532895.318662533
1626596.71995021532969.3306536171626610.87543371533055.677921871
#Sta/Elev= 30
       0  808.24    11.5  804.97    28.8  797.82      42   793.2    71.7  781.06
    88.2  773.04   104.8  767.31   121.4  757.67   131.3  756.05   141.3  755.82
   144.6  754.72   151.2   750.7  153.44 750.028   161.2  748.63   171.1  748.41
   181.1  748.82  185.43750.0251   197.7  754.36     211  756.17   240.9  756.36
   254.2  755.52   297.5  754.91   330.7  756.33   347.3  755.91   350.7  756.74
     364  762.09   376.4  768.56   387.2  772.75   397.2  777.83   425.1  787.38
#Mann= 5, -1 ,  0
       0     0.1       0  153.44   0.045       0  185.43     0.1       0
  202.61    0.06       0  387.61     0.1       0
#XS Ineff= 2 , 0
                          239.35          759.65
Permanent Ineff=
       F       F
Bank Sta=153.44,185.43
XS Rating Curve= 0 ,0
Exp/Cntr(USF)=0,0
Exp/Cntr=0.3,0.1

Type RM Length L Ch R = 1 ,10190   ,300.2,302.5,299.4
XS GIS Cut Line= 6
1626235.13528141532792.538146168 1626271.2277289532872.197435661
1626302.16401875 532940.477810921626345.27220024533030.969755917
1626380.29936115533100.1435020871626424.60340641533180.196819662
#Sta/Elev= 30
       0   812.2     6.5   809.6    24.5  799.62    30.2  796.89    46.1  789.91
    60.6  784.96    67.8  781.29    71.4  778.67    74.9  774.76    78.6  767.17
    82.3  758.09    84.8   753.6    87.2  750.62   90.43748.2433    94.7  746.99
   104.6  746.63   118.2  746.81   121.8  747.35  123.89748.2423     129  750.33
   132.6   750.8   172.3  752.51   299.9  753.09     333  754.77   374.1  755.52
   391.3  757.49   408.9  757.29   413.1   758.5   422.4  764.64   431.7  769.52
#Mann= 4, -1 ,  0
       0     0.1       0   90.43   0.045       0  123.89     0.1       0
  182.42    0.06       0
#XS Ineff= 2 , 0
                          254.51          755.98
Permanent Ineff=
       F       F
Bank Sta=90.43,123.89
XS Rating Curve= 0 ,0
Exp/Cntr(USF)=0,0
Exp/Cntr=0.3,0.1

Type RM Length L Ch R = 1 ,9887    ,566.1,600.6,627.2
XS GIS Cut Line= 6
1625939.55277893 532896.968296261625986.93063693532970.818870336
1626023.35477668533036.3800909221626071.91799976533123.796582758
1626108.34082717533189.3584595021626150.83385243 533265.84780784
#Sta/Elev= 30
       0  805.11      35  807.61      51  805.32    72.3  800.01    81.8  798.45
    96.2  794.62   108.3  789.56   121.8  785.18     127  782.32   130.8  779.72
   134.6   776.5   138.3  772.48   144.5     765   148.8  760.95   160.8   752.9
   164.6  750.71   175.8   748.5  184.92745.9565   194.6  745.03   209.6  744.72
   220.9  745.02  227.46745.9571   233.7  747.51   239.6  748.37   265.9  750.07
   318.5  750.67   329.7  751.42   352.2  752.14   398.8  751.66   425.2  752.06
#Mann= 4, -1 ,  0
       0     0.1       0  182.74    0.06       0  184.92   0.045       0
  227.46    0.06       0
Bank Sta=184.92,227.46
XS Rating Curve= 0 ,0
Exp/Cntr(USF)=0,0
Exp/Cntr=0.3,0.1

Type RM Length L Ch R = 1 ,9287    ,259.1,271,279.2
XS GIS Cut Line= 6
1625909.86718824532913.5217610911625681.63512627532978.143877879
1625589.83956759533026.9772225921625501.09269784533073.080804929
1625434.12104701533106.8445169181625355.98832926533146.235186175
#Sta/Elev= 30
       0  792.73    11.8  787.68    39.1  778.55    59.6  769.62    66.4  765.67
    76.6  756.21    83.4  750.97    93.7  747.32   148.2  744.76   280.8  745.87
   294.8  742.75   348.3  744.22   359.4  741.19   371.1  741.67     376740.4275
   381.6  739.12   403.8  738.73  411.41740.4235   414.8   742.9   422.2  751.14
   429.6  756.31   441.6  757.66   455.4  757.34   458.7  758.38   470.1  765.72
   495.4  774.61   536.3  793.52     562  810.27   581.9   818.1   603.7   832.2
#Mann= 7, -1 ,  0
       0     0.1       0     220    0.05       0   247.2     0.1       0
   317.2    0.06       0     376   0.045       0  411.41    0.06       0
  526.19     0.1       0
#XS Ineff= 2 , 0
          234.01  751.84
Permanent Ineff=
       F       F
Bank Sta=376,411.41
XS Rating Curve= 0 ,0
Exp/Cntr(USF)=0,0
Exp/Cntr=0.3,0.1

Type RM Length L Ch R = 1 ,9016    ,232.4,224.5,215.4
XS GIS Cut Line= 2
1625872.73657613532819.5165000971625427.55711042532782.066263791
#Sta/Elev= 30
       0  779.42     7.1  778.25    13.7   775.6    30.1  763.82      40  757.67
    46.6  754.67    63.1  749.16    79.5  746.47      96  741.91   125.6  742.89
   158.5  741.57   168.4  742.41   194.8     743   224.4  741.57   247.4  742.04
   316.6   741.6   326.7  742.18  351.14738.3912   379.1  736.47   385.7  737.36
  386.89738.3938   392.3  744.13   395.6  746.79   398.9  747.99   418.6   748.5
   421.9  750.15   428.5  759.15   435.1  767.13   441.7  773.12   446.8  776.76
#Mann= 6, -1 ,  0
       0     0.1       0     210    0.05       0     270     0.1       0
  351.14   0.045       0  386.89     0.1       0     390    0.06       0
Bank Sta=351.14,386.89
XS Rating Curve= 0 ,0
Exp/Cntr(USF)=0,0
Exp/Cntr=0.3,0.1

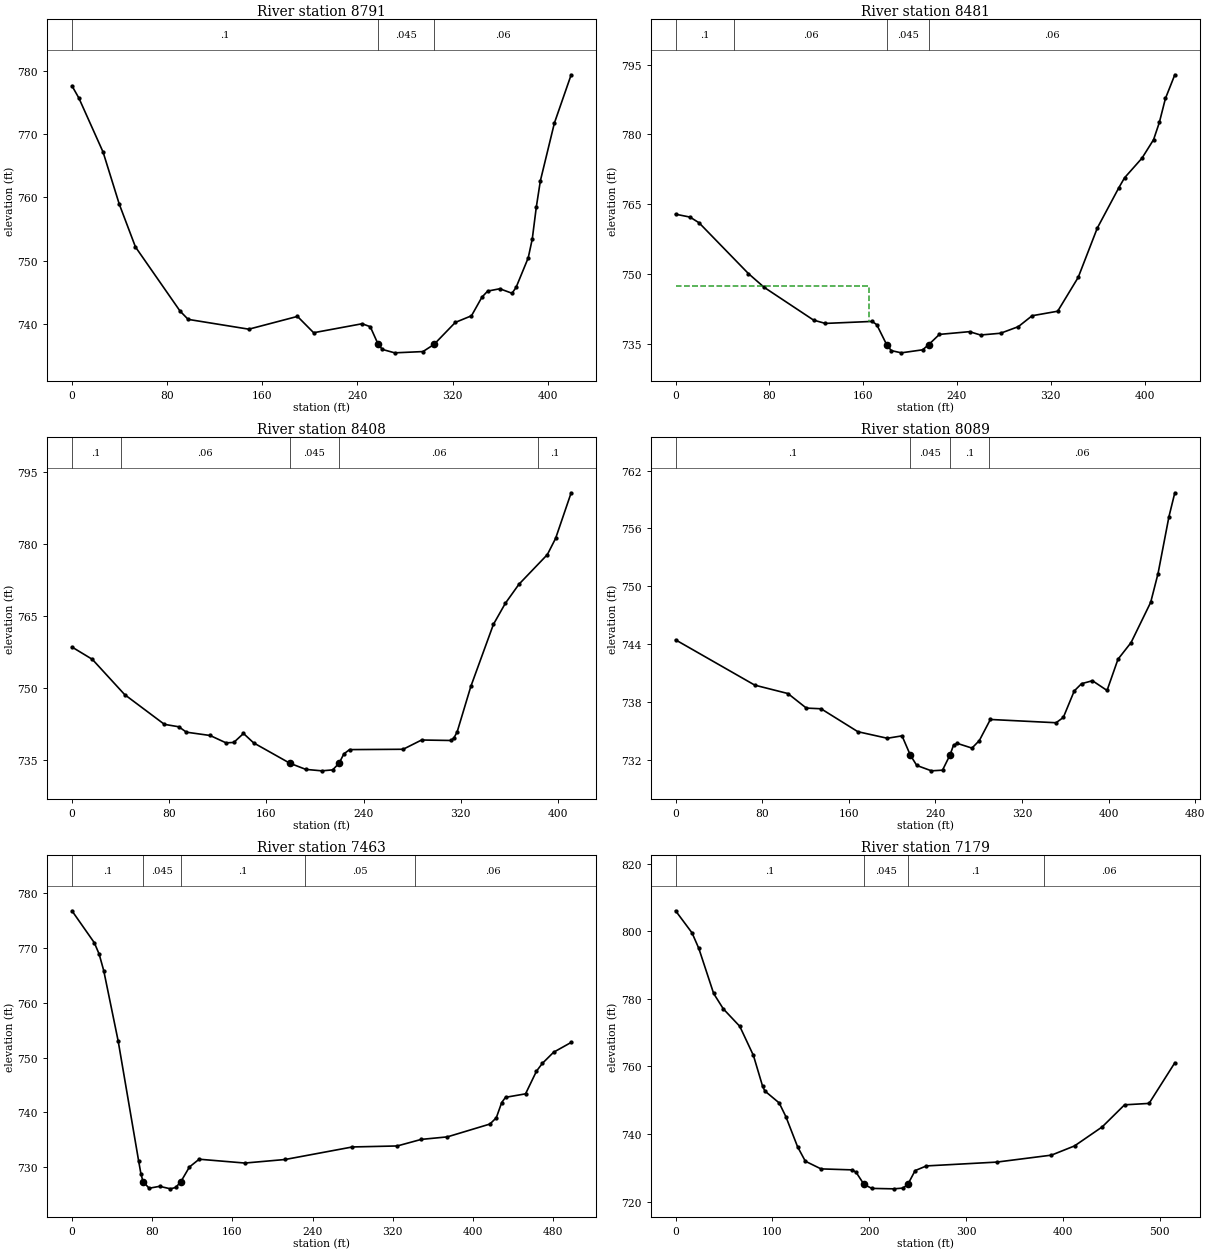
Type RM Length L Ch R = 1 ,8791    ,306.8,310.4,293.4
XS GIS Cut Line= 2
1625822.04099338532495.4767051591625417.43126728532607.124176483
#Sta/Elev= 30
       0  777.65     5.8  775.72    26.2  767.16    39.8  758.93    53.4  752.17
    90.9  742.03    97.7  740.72   148.7  739.17   189.6  741.19   203.2  738.61
     244  740.03   250.8  739.56   257.5736.7559     261  735.97   271.3  735.43
   295.1  735.63  304.38736.7576   322.3  740.24   335.9  741.29   344.7  744.24
   349.5  745.19   359.7  745.56     370  744.85   373.4  745.78   383.6  750.45
     387  753.43   390.4  758.48   393.8  762.62   405.6  771.76   419.7  779.39
#Mann= 3, -1 ,  0
       0     0.1       0   257.5   0.045       0  304.38    0.06       0
Bank Sta=257.5,304.38
XS Rating Curve= 0 ,0
Exp/Cntr(USF)=0,0
Exp/Cntr=0.3,0.1

Type RM Length L Ch R = 1 ,8481    ,68.3,72.4,68.2
XS GIS Cut Line= 6
1625607.43400897532167.7026097991625553.90032337532237.360278882
1625504.64025129532294.114102385 1625437.0655833532368.152012057
1625386.77270488532423.8100372181625328.74034063532489.337793313
#Sta/Elev= 30
       0  762.87    12.3  762.25      20  761.03    62.1  750.12    75.6  747.15
   117.7  740.12   127.7  739.41   167.7  739.84   171.6  739.13  180.04734.8439
     184  733.57   192.5  733.09   210.7  733.74  215.85734.8433     225  737.05
   250.7  737.64   260.1  736.92   277.2   737.3   292.3  738.71   304.1  741.06
   325.9  742.03   343.4   749.3   359.7   759.9     378  768.53   382.9  770.68
   397.8  774.91   407.7  778.89   412.6  782.57   417.8  787.73   425.8  792.82
#Mann= 4, -1 ,  0
       0     0.1       0      50    0.06       0  180.04   0.045       0
  215.85    0.06       0
#XS Ineff= 2 , 0
          165.35  747.41
Permanent Ineff=
       F       F
Bank Sta=180.04,215.85
XS Rating Curve= 0 ,0
Exp/Cntr(USF)=0,0
Exp/Cntr=0.3,0.1

Type RM Length L Ch R = 1 ,8408    ,328.3,319.6,310.5
XS GIS Cut Line= 5
1625587.19507771532155.6093089491625469.28511941532231.633466128
1625396.67171788532311.7178560481625346.37883946532367.375881209
1625288.34647521532432.903637304
#Sta/Elev= 30
       0  758.62    16.8  756.05    43.4  748.71    76.1  742.52      88  742.01
    94.2  740.89   113.7   740.2   126.8  738.67   133.2  738.75   141.2  740.62
   149.5  738.67  179.35 734.425   192.5  733.14   205.7  732.84   214.6  733.04
  219.87 734.425   223.8  736.36   228.5  737.26   272.6  737.33   287.8  739.26
   311.9  739.16   314.4  739.68   317.1  740.98   328.3   750.4   346.9  763.33
   356.7  767.71   367.9  771.68   391.3  777.86   398.1  781.24   410.9  790.73
#Mann= 5, -1 ,  0
       0     0.1       0      40    0.06       0  179.35   0.045       0
  219.87    0.06       0  383.41     0.1       0
Bank Sta=179.35,219.87
XS Rating Curve= 0 ,0
Exp/Cntr(USF)=0,0
Exp/Cntr=0.3,0.1

Type RM Length L Ch R = 1 ,8089    ,632.1,625.9,598
XS GIS Cut Line= 4
1625215.15330938531901.0416023191625136.84679673 532189.32672633
1625120.22511082532262.4617506681625100.83407348532347.786055085
#Sta/Elev= 30
       0  744.43    73.2  739.73   103.8  738.86   120.8  737.35   134.4  737.28
   168.4   734.9   195.6  734.22   209.2  734.47  216.87 732.469   222.8   731.4
   236.4  730.84   246.6  730.91  253.44732.4672   256.8  733.51   260.2  733.69
   273.8   733.2   280.6  733.98   290.8  736.17   351.5  735.83   358.2  736.38
   368.3  739.13     375  739.88   385.1  740.19   398.6  739.18   408.7  742.42
   420.8  744.15   438.9  748.32   445.7  751.31   455.8  757.22   461.2  759.69
#Mann= 4, -1 ,  0
       0     0.1       0  216.87   0.045       0  253.44     0.1       0
     290    0.06       0
Bank Sta=216.87,253.44
XS Rating Curve= 0 ,0
Exp/Cntr(USF)=0,0
Exp/Cntr=0.3,0.1

Type RM Length L Ch R = 1 ,7463    ,279.6,283.9,286.2
XS GIS Cut Line= 5
1624587.11006344532070.3243672041624647.61322327532133.534870707
 1624699.4726996 532187.716192791624769.83673209532258.791838043
1624904.47506265 532452.00160304
#Sta/Elev= 30
       0  776.81    22.3  770.98    27.1  768.92    31.7  765.89    46.1  753.04
    66.5  731.16    68.8  728.79   70.89727.3644      77  726.14    87.5  726.49
    98.3  726.03   103.6  726.29  108.73727.3627   117.2  730.02   126.9  731.44
   172.5  730.74   212.7  731.39   279.8  733.68   324.5  733.86   348.5  735.06
   374.5  735.52   416.9  737.86   423.3     739   428.7  741.79   432.5  742.74
   452.5  743.38   463.4  747.52   469.2  748.93   480.5  750.98     498  752.77
#Mann= 5, -1 ,  0
       0     0.1       0   70.89   0.045       0  108.73     0.1       0
   232.5    0.05       0  342.51    0.06       0
Bank Sta=70.89,108.73
XS Rating Curve= 0 ,0
Exp/Cntr(USF)=0,0
Exp/Cntr=0.3,0.1

Type RM Length L Ch R = 1 ,7179    ,292,290.4,286.6
XS GIS Cut Line= 2
1624333.61218186532164.5555707011624633.60928586532583.853762406
#Sta/Elev= 30
       0  806.03      17  799.49      24  794.89    39.3  781.57    49.3  777.01
    66.3  771.85    80.4  763.23    89.8  754.19    92.2  752.72     107  749.19
   113.9  745.14     126  736.22     134  731.95   150.2  729.68   182.4  729.39
   186.5  728.65  194.58725.0894   202.7  723.91   225.4  723.78   234.9  724.01
  239.85725.0904   247.4  729.18   259.1  730.56   331.7  731.69   388.2  733.75
     412  736.47   440.6   742.1   463.7  748.63     489  749.05   515.6  761.06
#Mann= 4, -1 ,  0
       0     0.1       0  194.58   0.045       0  239.85     0.1       0
     380    0.06       0
Bank Sta=194.58,239.85
XS Rating Curve= 0 ,0
Exp/Cntr(USF)=0,0
Exp/Cntr=0.3,0.1

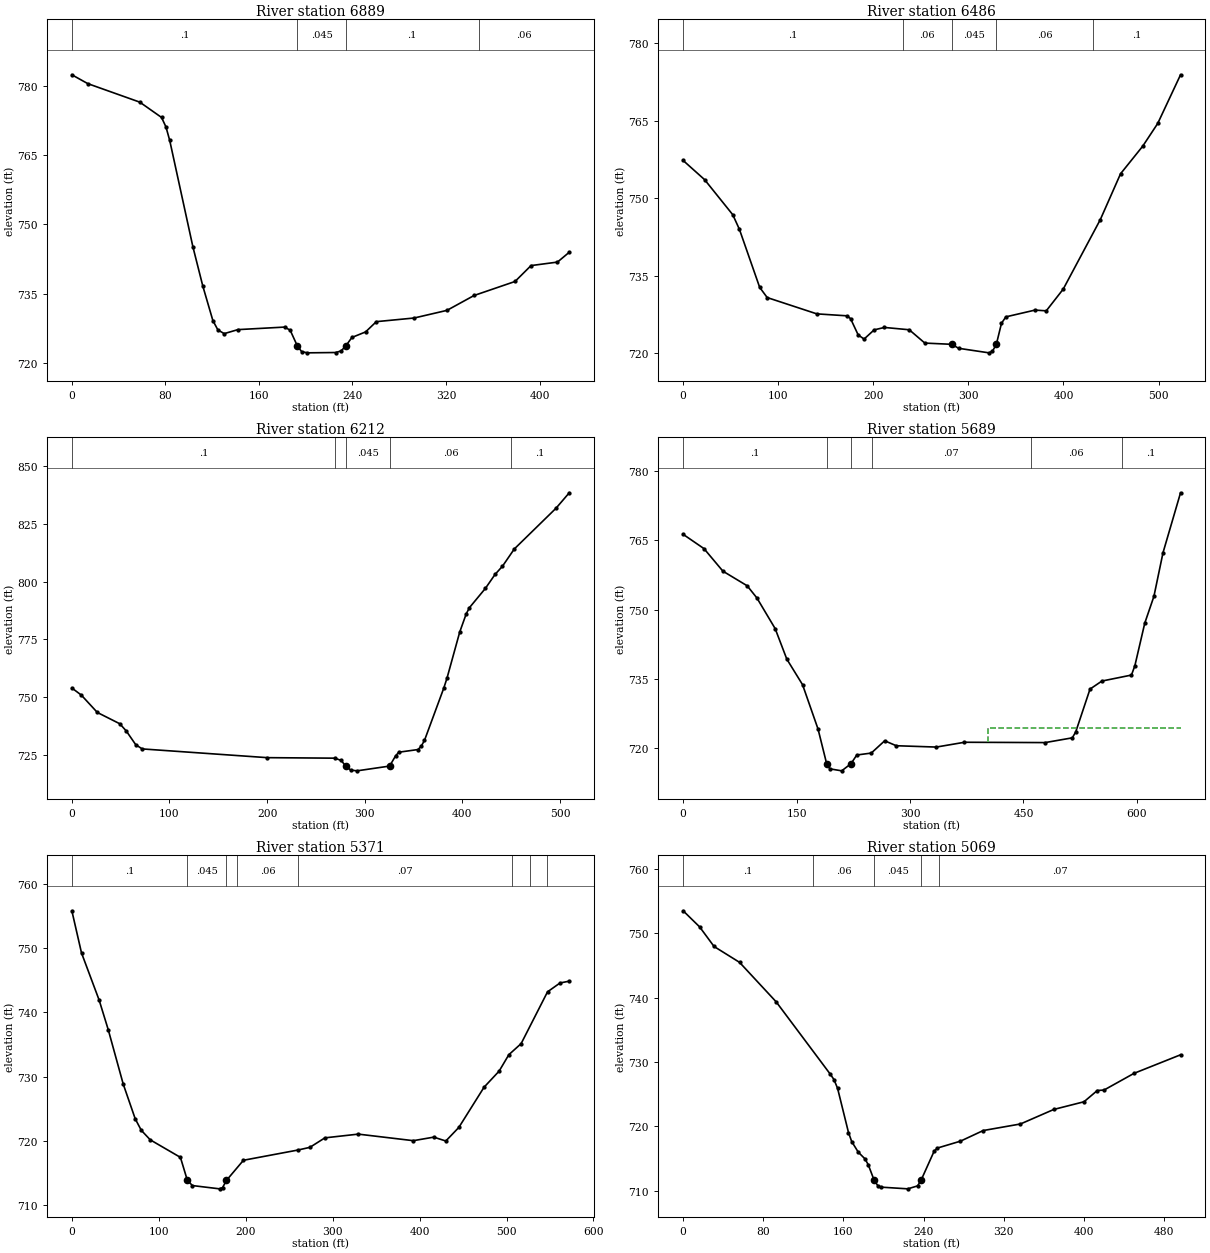
Type RM Length L Ch R = 1 ,6889    ,390.5,402.8,406.7
XS GIS Cut Line= 6
1624101.69424993532364.5549910071624157.69249751532432.075197175
1624205.94272909532489.7082840061624273.25853933 532563.70026201
1624325.10029918532617.8983163391624385.58180551532681.130145252
#Sta/Elev= 30
       0  782.48    13.7  780.55    58.1  776.54    76.7  773.22    80.5  771.15
    83.7  768.22   103.5  745.16     112  736.61   120.6  729.13   124.9  727.09
   130.3  726.29     142  727.16   181.9  727.71   186.7  727.04  192.77723.6627
   196.5  722.39   201.4  722.12   225.7  722.19   230.3  722.54  234.41723.6638
   239.5  725.46   251.2  726.66   260.4  728.89   292.7  729.68   320.8  731.34
     344  734.57     379  737.61   392.7  741.06   415.3  741.82   425.4  743.96
#Mann= 4, -1 ,  0
       0     0.1       0  192.77   0.045       0  234.41     0.1       0
  347.92    0.06       0
Bank Sta=192.77,234.41
XS Rating Curve= 0 ,0
Exp/Cntr(USF)=0,0
Exp/Cntr=0.3,0.1

Type RM Length L Ch R = 1 ,6486    ,258.1,274.3,279.1
XS GIS Cut Line= 3
1623830.92427258 532464.315470161623838.41707957532564.991496237
1623999.47893592532955.220682986
#Sta/Elev= 30
       0  757.32    22.6   753.6    52.2  746.81    59.2  743.98    80.5  732.74
    88.4  730.76   140.6   727.6   172.5  727.22   176.1  726.67   184.1  723.52
   190.3  722.72   200.9   724.5   211.7  724.97   237.8  724.52   254.2  721.94
   282.6   721.7   289.7  720.93   321.6  720.05   325.2  720.33  329.38721.6889
   334.8  725.78   339.4  727.02     370  728.33   381.9  728.19   399.7  732.39
   438.7  745.85     460  754.74   483.3  760.08   499.1  764.49   523.1  773.92
#Mann= 5, -1 ,  0
       0     0.1       0  230.95    0.06       0   282.6   0.045       0
  329.38    0.06       0  430.95     0.1       0
Bank Sta=282.6,329.38
XS Rating Curve= 0 ,0
Exp/Cntr(USF)=0,0
Exp/Cntr=0.3,0.1

Type RM Length L Ch R = 1 ,6212    ,533.5,522.6,516.3
XS GIS Cut Line= 2
 1623672.9610667532480.4279420471623646.56398687532989.282982701
#Sta/Elev= 30
       0  753.99     9.7  750.92    26.1  743.41    49.1  738.52    55.7  735.42
    65.5  729.43    72.1  727.64   200.2  723.86   269.2  723.64   275.8  722.68
  280.52720.2223   285.6  718.49   292.1  718.16  325.48720.2227   331.6  724.64
   334.9  726.22   354.6  727.37   357.9  728.85   361.2  731.33   380.9  753.87
   384.2  758.16   397.3   778.2   403.9     786   407.2  788.71   423.6  797.08
   433.5  803.12   441.1  806.67   453.2  814.12   495.9  831.73   509.5  838.42
#Mann= 5, -1 ,  0
       0     0.1       0     270    0.06       0  280.52   0.045       0
  325.48    0.06       0     450     0.1       0
Bank Sta=280.52,325.48
XS Rating Curve= 0 ,0
Exp/Cntr(USF)=0,0
Exp/Cntr=0.3,0.1

Type RM Length L Ch R = 1 ,5689    ,329.9,317.6,304.7
XS GIS Cut Line= 3
1623091.71902708532504.4248792671623128.51550961532586.266148964
1623437.34136327533062.918002279
#Sta/Elev= 30
       0  766.31    27.6  763.21    52.6  758.33    84.7  755.16    97.5  752.54
   121.7  745.88   137.1  739.27   157.9  733.74   178.4  724.12  189.75716.6331
   194.1   715.5   209.7  715.07  222.05716.6326   229.6   718.5   248.8  718.92
   266.5  721.58   281.8  720.51   334.8  720.22     372  721.26   478.7  721.19
   514.6  722.22   519.1   723.5     538  732.78   553.7  734.52   592.8  735.82
   597.3  737.84   610.4  747.07   622.5  752.87   634.5  762.32   657.7  775.31
#Mann= 6, -1 ,  0
       0     0.1       0  189.75   0.045       0  222.05     0.1       0
  249.73    0.07       0  459.73    0.06       0  579.73     0.1       0
#XS Ineff= 2 , 0
                          403.32          724.37
Permanent Ineff=
       F       F
Bank Sta=189.75,222.05
XS Rating Curve= 0 ,0
Exp/Cntr(USF)=0,0
Exp/Cntr=0.3,0.1

Type RM Length L Ch R = 1 ,5371    ,311.1,302,293
XS GIS Cut Line= 3
1622853.70554331532873.1971667321623144.19156951532971.449335189
 1623354.8925606533132.986282719
#Sta/Elev= 30
       0  755.81    11.1  749.25    31.4   741.9    41.8  737.32    59.1  728.82
    72.9  723.41    79.9  721.62    90.2  720.14   124.9  717.41  132.86713.8343
   138.7  713.02   169.9  712.51   173.4  712.71  177.89713.8339   197.4  716.96
     260  718.55   273.8  718.97   291.1  720.45   329.5  721.03   392.8  720.01
   416.3  720.56   430.2  719.96   445.2  722.08   474.2  728.34   491.5  730.84
   502.7   733.4   516.8  735.12   547.2  743.19   561.6  744.57   572.2  744.85
#Mann= 8, -1 ,  0
       0     0.1       0  132.86   0.045       0  177.89     0.1       0
     190    0.06       0     260    0.07       0  506.65    0.06       0
  526.65    0.07       0  546.65     0.1       0
Bank Sta=132.86,177.89
XS Rating Curve= 0 ,0
Exp/Cntr(USF)=0,0
Exp/Cntr=0.3,0.1

Type RM Length L Ch R = 1 ,5069    ,122.8,123.8,126.3
XS GIS Cut Line= 4
1622707.80823717533142.5184245921622857.19013009533212.751874557
1622981.45201752533203.939689454 1623184.9473722533241.885504912
#Sta/Elev= 30
       0  753.49    16.4     751    30.9  747.94    56.3  745.48    92.9  739.34
   147.1  728.06   150.6  727.26   154.2   725.9   165.1  719.03   168.3  717.63
   174.9  715.97   181.5  714.95   184.8  714.04  190.72711.6096   194.7   710.7
   197.9  710.54   224.3  710.28   234.1  710.74  237.53711.6085   250.6  716.13
   253.9  716.62   276.9  717.69   299.6  719.34   336.8  720.36   370.1  722.62
   400.2  723.81   413.5  725.56   420.2  725.63   450.2  728.23   496.6  731.11
#Mann= 5, -1 ,  0
       0     0.1       0     130    0.06       0  190.72   0.045       0
  237.53    0.06       0  255.07    0.07       0
Bank Sta=190.72,237.53
XS Rating Curve= 0 ,0
Exp/Cntr(USF)=0,0
Exp/Cntr=0.3,0.1

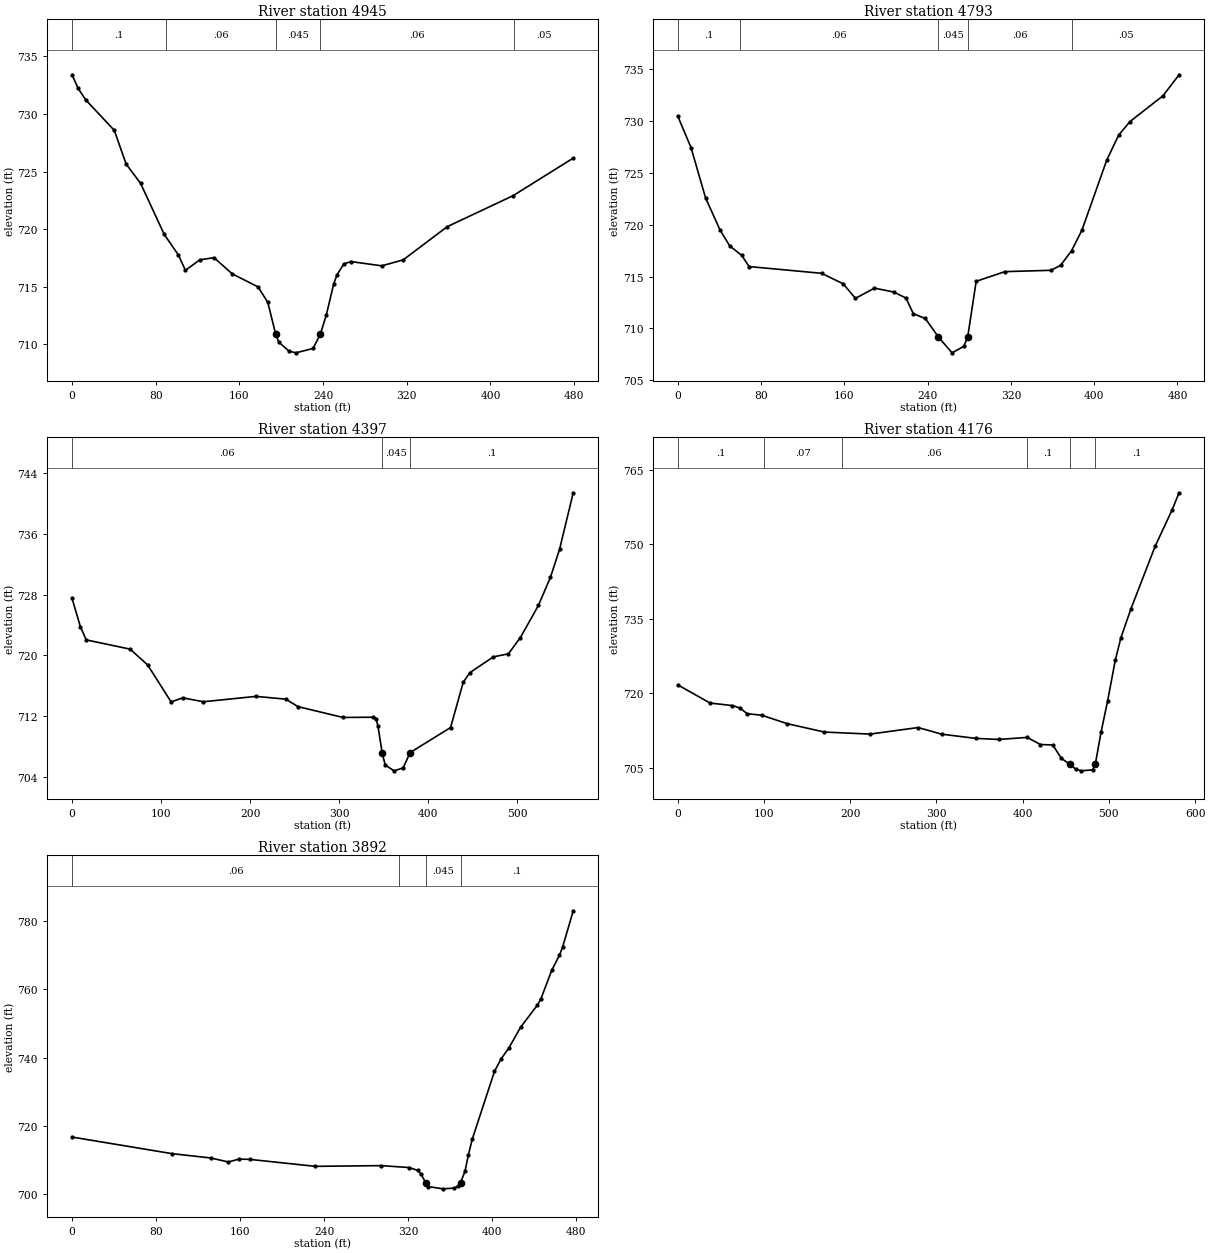
Type RM Length L Ch R = 1 ,4945    ,133.7,152.3,162.6
XS GIS Cut Line= 4
1622671.86653948533241.5975564881622827.96674379533327.507066358
1622942.15116414533325.413192642  1623122.068605 533375.24817982
#Sta/Elev= 30
       0  733.41     5.8  732.23      13  731.24    40.4  728.58    51.7  725.65
    65.5  723.98      88  719.56   101.6  717.76   108.4  716.42   122.1  717.33
   135.7  717.52   153.2  716.11   177.8  714.98   187.1  713.64  194.71710.8631
   197.6  710.18   207.4   709.4     214  709.25   230.4  709.63  237.32 710.862
   243.1  712.55   250.1  715.23   253.3  716.04   259.9  716.98   266.5  717.18
   296.1  716.81   316.6  717.33   358.6  720.21   421.7  722.91   479.1  726.17
#Mann= 5, -1 ,  0
       0     0.1       0      90    0.06       0  194.71   0.045       0
  237.32    0.06       0  422.38    0.05       0
Bank Sta=194.71,237.32
XS Rating Curve= 0 ,0
Exp/Cntr(USF)=0,0
Exp/Cntr=0.3,0.1

Type RM Length L Ch R = 1 ,4793    ,385.8,395.9,402.1
XS GIS Cut Line= 4
1622615.37184722533271.7650904351622841.02485526533497.214471087
1622896.96929717533547.1667990091622960.19554867533607.731310427
#Sta/Elev= 30
       0  730.43    12.7   727.4    26.7  722.55    40.6  719.47    49.8  717.95
    61.4  717.04    68.4  715.96   138.1  715.31   158.8   714.3   170.6   712.9
   188.9  713.88   207.3  713.51   219.1  712.93   226.3  711.41   237.7  710.96
  250.11709.2015   263.4  707.65   274.8  708.28  278.49709.2023   286.6  714.54
   314.2  715.47   358.5   715.6   367.7  716.08   378.2  717.48   388.1  719.44
     412   726.2   423.4  728.61   434.3  729.92   466.1  732.41   481.5  734.43
#Mann= 5, -1 ,  0
       0     0.1       0      60    0.06       0  250.11   0.045       0
  278.49    0.06       0  378.98    0.05       0
Bank Sta=250.11,278.49
XS Rating Curve= 0 ,0
Exp/Cntr(USF)=0,0
Exp/Cntr=0.3,0.1

Type RM Length L Ch R = 1 ,4397    ,217.6,221,221.3
XS GIS Cut Line= 3
1622414.18175293533277.9586967021622424.74985443 533492.91056025
1622506.40449382533830.523318125
#Sta/Elev= 30
       0  727.52     9.4  723.77    15.9  722.04    65.2  720.82    84.9  718.73
   111.2  713.86   124.3   714.4   147.3  713.88   206.5  714.59     240  714.22
   253.6  713.24   304.1  711.81   338.1  711.84   341.2  711.64   343.3  710.74
  348.08 707.181   351.5  705.54   361.5  704.77   371.6  705.15  379.58 707.184
   424.9  710.48   439.1  716.44   446.6  717.72   472.9   719.8   489.8   720.2
   503.3  722.35   523.5  726.58     537  730.28   547.2  733.97   562.6  741.44
#Mann= 3, -1 ,  0
       0    0.06       0  348.08   0.045       0  379.58     0.1       0
Bank Sta=348.08,379.58
XS Rating Curve= 0 ,0
Exp/Cntr(USF)=0,0
Exp/Cntr=0.3,0.1

Type RM Length L Ch R = 1 ,4176    ,277.2,284.1,290.4
XS GIS Cut Line= 5
1622208.79299023533276.615890382 1622248.9748531533548.428479656
1622267.50801192533691.4146040181622274.96961117533766.042735602
1622283.67497434533853.108506361
#Sta/Elev= 30
       0  721.68    37.4  718.03    63.3  717.52    71.9  717.04    80.5  715.88
    97.1  715.59   126.8  713.88     170  712.19   223.1  711.78   278.7   713.1
   305.9  711.77   345.6  710.91   372.1   710.7   405.2  711.11   420.6  709.68
   434.9  709.59   444.8  706.91  454.41705.7275   461.3  704.75   467.9  704.38
     481  704.58  484.29705.7261   490.9  712.14   498.6  718.51   507.4  726.64
     514  731.21   525.5  736.96   553.6  749.58   573.4  756.94   581.4  760.37
#Mann= 6, -1 ,  0
       0     0.1       0     100    0.07       0     190    0.06       0
  404.77     0.1       0  454.41   0.045       0  484.29     0.1       0
Bank Sta=454.41,484.29
XS Rating Curve= 0 ,0
Exp/Cntr(USF)=0,0
Exp/Cntr=0.3,0.1

Type RM Length L Ch R = 1 ,3892    ,304,307.7,310.9
XS GIS Cut Line= 4
1622091.16292704533341.5271455661622058.80352339533499.875835917
1621979.69915009533727.3232628411621957.64243567533799.006518424
#Sta/Elev= 30
       0   716.7    95.4  711.83   132.2  710.57   148.9   709.4     159  710.24
   169.3  710.16   231.8  708.12   294.4  708.33   321.1  707.77   329.1  706.94
   332.6  705.78  336.83703.3174   339.5  702.19   353.4  701.53   363.8  701.75
   367.5  702.27  370.02 703.319   374.3   706.7   377.6  711.56   381.2  716.06
   402.4  735.96   408.8  739.67   415.8  742.65   427.2  748.85   443.2  755.33
   446.7  757.26     457   765.6   464.3  769.99   467.3  772.38   477.4  782.99
#Mann= 4, -1 ,  0
       0    0.06       0  311.62     0.1       0  336.83   0.045       0
  370.02     0.1       0
Bank Sta=336.83,370.02
XS Rating Curve= 0 ,0
Exp/Cntr(USF)=0,0
Exp/Cntr=0.3,0.1