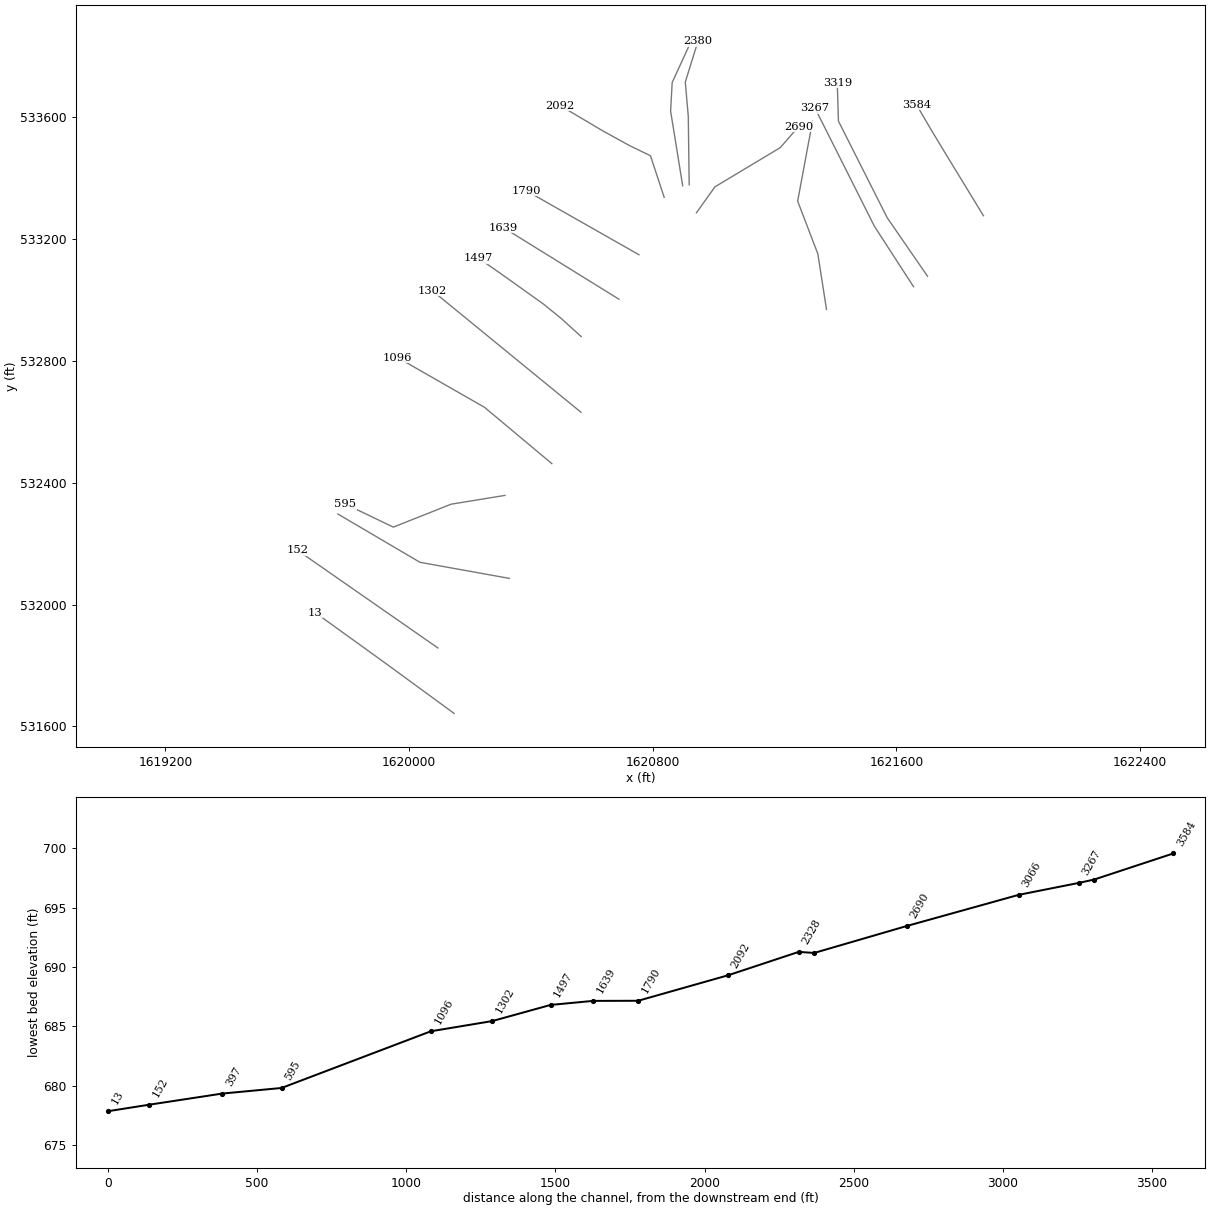
HEC-RAS study LtlGraveCk.prj: LtlGraveCk

--- LtlGraveCk.g01 (geometry) --- (continued)

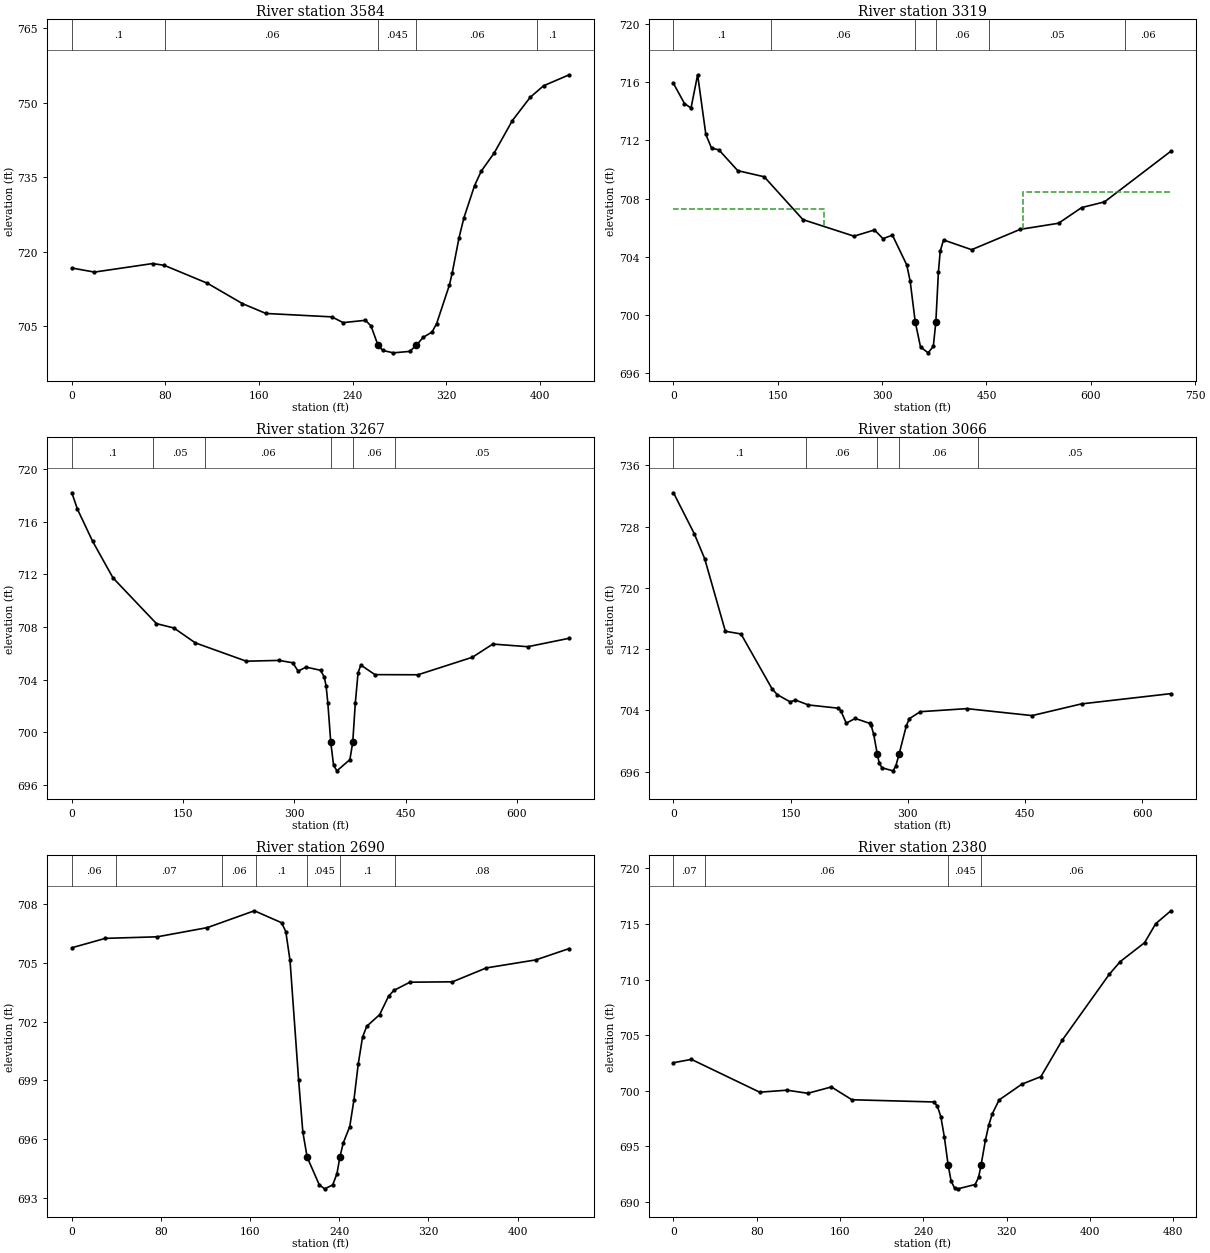
Type RM Length L Ch R = 1 ,3584    ,266.4,265.4,263.4
XS GIS Cut Line= 6
 1621885.8951793533276.9942853861621840.31817071533351.686721306
1621801.25263205 533415.709231061621749.16579397533501.072905477
1621710.55694729533565.3739579731621666.44548696533640.961077135
#Sta/Elev= 30
       0  716.68    19.3  715.86      69  717.58      79  717.22   115.9   713.6
   145.8   709.5   165.8  707.52   222.2  706.83   231.8  705.67   250.9  706.14
   255.6  705.01  261.61701.0878   265.7  700.06   274.7  699.58   288.7  699.87
  294.24701.0865   300.2   702.7   307.8  703.79   311.7  705.49   322.6  713.25
     325  715.69   330.8  722.76     335   726.8   344.1   733.3   349.8  736.21
   360.9  739.89   376.4  746.41   391.6  751.09     403  753.42     425  755.64
#Mann= 5, -1 ,  0
       0     0.1       0      80    0.06       0  261.61   0.045       0
  294.24    0.06       0   397.5     0.1       0
Bank Sta=261.61,294.24
XS Rating Curve= 0 ,0
Exp/Cntr(USF)=0,0
Exp/Cntr=0.3,0.1

Type RM Length L Ch R = 1 ,3319    ,50.7,52.4,50.9
XS GIS Cut Line= 4
1621702.26859483533078.2771050311621569.77706967 533270.54366459
1621409.81464334533587.5497995261621405.89181336 533714.09057023
#Sta/Elev= 30
       0  715.92    15.8  714.54    25.2  714.23    34.7  716.52    46.5  712.42
    54.7  711.47    65.3  711.35    92.4  709.92   130.4   709.5   186.1  706.55
   259.6  705.41     289  705.84   301.2  705.24   314.8  705.48   335.4  703.43
   340.3  702.31   347.6  699.51   355.2  697.78   366.2  697.38   373.6  697.83
  377.23 699.507   380.9  702.93   383.5  704.38   388.3  705.15   428.7  704.48
   498.5  705.88   553.6   706.3   586.9  707.38   619.7  707.77   715.2  711.26
#Mann= 6, -1 ,  0
       0     0.1       0     140    0.06       0   347.6   0.045       0
  377.23    0.06       0   453.5    0.05       0  648.57    0.06       0
#XS Ineff= 2 , 0
          216.61  707.26  501.95          708.44
Permanent Ineff=
       F       F
Bank Sta=347.6,377.23
XS Rating Curve= 0 ,0
Exp/Cntr(USF)=0,0
Exp/Cntr=0.3,0.1

Type RM Length L Ch R = 1 ,3267    ,203.1,200.4,200.6
XS GIS Cut Line= 3
1621656.34495335533043.9065561521621527.88441503533242.219595959
1621332.75901076533630.340432652
#Sta/Elev= 30
       0  718.19     7.5  716.95    28.1   714.5    55.5  711.73   114.1  708.26
   137.6  707.93   166.5   706.8   235.2  705.41   279.4  705.47   297.8  705.29
   305.1  704.66   315.9  704.96   335.4  704.72   340.3  704.21   342.8  703.55
   345.2  702.22  349.13699.2529   352.9  697.51   357.4  697.09   374.9  697.94
  378.75699.2463   382.2  702.22   385.9  704.52   389.6  705.12   408.7  704.39
   466.7  704.38   540.1  705.71   567.6  706.71   614.8  706.51   670.7  707.15
#Mann= 6, -1 ,  0
       0     0.1       0     110    0.05       0     180    0.06       0
  349.13   0.045       0  378.75    0.06       0  436.28    0.05       0
Bank Sta=349.13,378.75
XS Rating Curve= 0 ,0
Exp/Cntr(USF)=0,0
Exp/Cntr=0.3,0.1

Type RM Length L Ch R = 1 ,3066    ,398.1,375.8,360.5
XS GIS Cut Line= 4
1621370.59457218532969.0624078921621342.25082515533151.374629869
1621275.87721031533324.8163405821621324.65924894533586.782912124
#Sta/Elev= 30
       0  732.43    26.6  727.08    39.9  723.82    66.4  714.33    86.4  713.98
   126.1  706.82   132.8  706.05   149.4   705.1   156.1  705.34   172.7   704.7
   210.6  704.28   214.1  703.95   221.2  702.32   232.6  702.94     251   702.3
   252.8   702.1   256.3  700.85  260.88698.2619   263.3  697.12   266.8  696.49
   280.9  696.09   284.4  696.66  288.73 698.262     298  701.97     302  702.92
     316  703.82   375.5  704.22     459  703.31   522.3  704.84   636.7  706.18
#Mann= 5, -1 ,  0
       0     0.1       0     170    0.06       0  260.88   0.045       0
  288.73    0.06       0  390.21    0.05       0
Bank Sta=260.88,288.73
XS Rating Curve= 0 ,0
Exp/Cntr(USF)=0,0
Exp/Cntr=0.3,0.1

Type RM Length L Ch R = 1 ,2690    ,295.4,310.2,329.9
XS GIS Cut Line= 6
1620943.45384726533286.3891053351621004.34283309533371.869577423
1621068.65405618533410.4574267571621154.40355659533461.906798929
1621218.71543585 533500.493992091621278.84589301533569.413145587
#Sta/Elev= 30
       0  705.78      30  706.26    76.7  706.34   121.6  706.81   163.8  707.67
   188.2  707.06     192  706.61   195.8  705.13   203.5  699.03   207.3  696.36
  211.19695.0765   222.1  693.66   226.9  693.46   234.1  693.66   237.9  694.23
  240.51695.0742   243.6  695.81   249.4  696.64   253.2  698.02     257  699.83
   260.9  701.22   264.7  701.77   276.2  702.36   284.2   703.3     289   703.6
   303.4  704.02   341.6  704.04     372  704.75   416.4  705.16   446.4  705.74
#Mann= 7, -1 ,  0
       0    0.06       0      40    0.07       0  134.95    0.06       0
  164.95     0.1       0  211.19   0.045       0  240.51     0.1       0
  289.95    0.08       0
Bank Sta=211.19,240.51
XS Rating Curve= 0 ,0
Exp/Cntr(USF)=0,0
Exp/Cntr=0.3,0.1

Type RM Length L Ch R = 1 ,2380    ,54,51.7,49.5
XS GIS Cut Line= 4
1620919.69991012  533378.36935121620916.69996376533603.291686758
1620906.90528632533715.8675025561620948.49906878 533849.54665681
#Sta/Elev= 30
       0  702.53    17.2  702.83    82.8  699.88   109.1  700.06     129  699.78
   151.7  700.35   171.4   699.2   250.3     699   253.6  698.61   256.9  697.66
   260.2  695.87  263.87693.3393   266.7  691.89     270  691.27   273.3  691.19
   289.8  691.58   293.1  692.21  295.54693.3412   299.7  695.57     303  696.95
   306.3  697.93   312.8  699.18   334.7   700.6     353  701.28   373.6  704.57
   418.7  710.48   429.2  711.62   452.6  713.32   463.3  715.03   477.9  716.19
#Mann= 4, -1 ,  0
       0    0.07       0      30    0.06       0  263.87   0.045       0
  295.54    0.06       0
Bank Sta=263.87,295.54
XS Rating Curve= 0 ,0
Exp/Cntr(USF)=0,0
Exp/Cntr=0.3,0.1

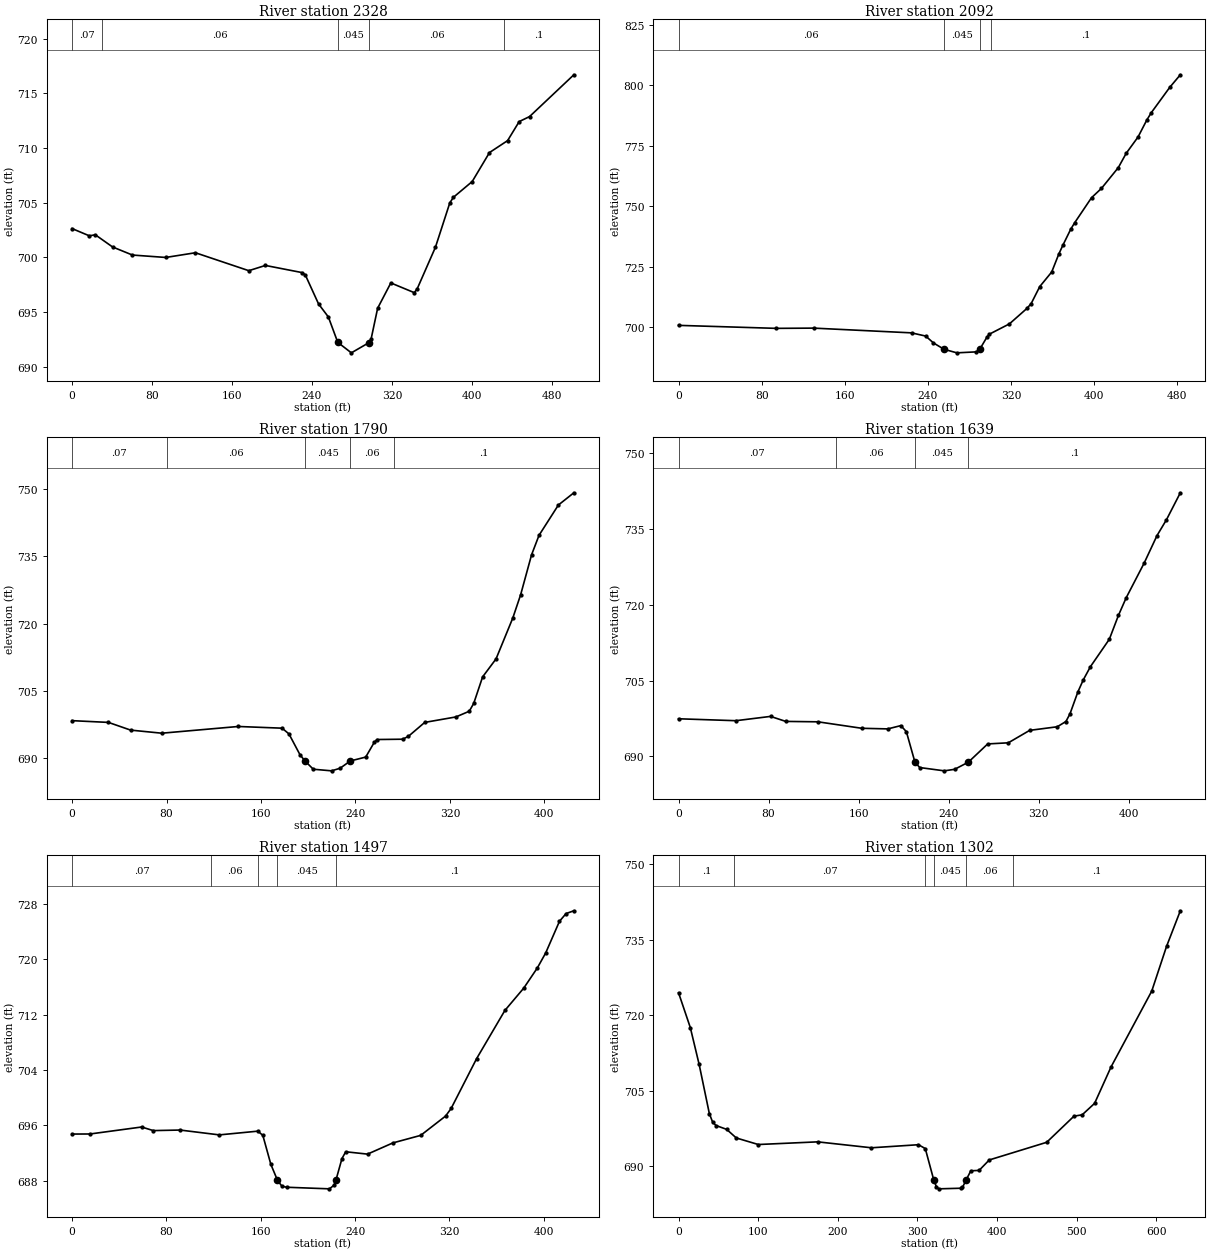
Type RM Length L Ch R = 1 ,2328    ,216.1,236.5,252.6
XS GIS Cut Line= 4
1620898.35841039533375.2901418371620858.68477035533620.629046367
1620863.86553462533714.371800567 1620930.4664046533859.403589615
#Sta/Elev= 30
       0  702.64    17.2  701.98    23.3  702.07    40.5  700.96    60.4  700.22
    93.7     700   123.4  700.43   176.8  698.79   193.4  699.27   229.9  698.62
   233.3  698.41   246.6  695.75   256.4  694.56   265.8  692.24   279.4  691.28
     297  692.21   299.2  692.56   305.7  695.36   318.9  697.67   342.4  696.78
   345.4  697.16   363.5  700.93   377.9  704.99   381.5   705.5   400.3  706.94
   417.6  709.59   435.7  710.68   447.3  712.42   457.7  712.88     502   716.7
#Mann= 5, -1 ,  0
       0    0.07       0      30    0.06       0   265.8   0.045       0
     297    0.06       0  432.41     0.1       0
Bank Sta=265.8,297
XS Rating Curve= 0 ,0
Exp/Cntr(USF)=0,0
Exp/Cntr=0.3,0.1

Type RM Length L Ch R = 1 ,2092    ,301.4,301.6,300.2
XS GIS Cut Line= 6
1620837.58299601533337.3555388451620792.60080251533473.802444428
1620723.53368342533507.3476529271620635.89671959533555.614616752
1620571.37486701533593.8497765061620496.09909892533638.457298845
#Sta/Elev= 30
       0  700.67      94  699.43   130.1  699.53   224.3  697.57   237.9  696.24
   245.4  693.39  255.64690.7669   267.9  689.31   286.6  689.71  289.91690.7653
   296.8  695.77   299.2  697.03   318.5  701.28   335.3  707.66   339.4  709.65
   347.7   716.7   359.2  722.73   366.1  730.22   369.9  733.75   377.5  740.41
   381.3  743.09   397.5  753.43   407.1   757.3   423.3  765.88   430.9   771.8
   442.3  778.54   450.7  785.53     455  788.56   472.8  799.05     483  804.26
#Mann= 4, -1 ,  0
       0    0.06       0  255.64   0.045       0  289.91    0.06       0
  300.45     0.1       0
Bank Sta=255.64,289.91
XS Rating Curve= 0 ,0
Exp/Cntr(USF)=0,0
Exp/Cntr=0.3,0.1

Type RM Length L Ch R = 1 ,1790    ,151.6,151,149.9
XS GIS Cut Line= 6
1620754.68814868 533148.861493261620678.61152917533192.088769004
1620613.40234201533229.1398760081620526.45730592533278.541680083
1620461.24811876533315.5924590081620385.17084309533358.818750501
#Sta/Elev= 30
       0  698.36    30.8  697.97    49.6  696.25      76  695.56   140.8  697.06
   177.9  696.68   183.7   695.4     193  690.77  197.27689.3629   204.3  687.52
   219.8  687.16     227  687.74  235.65689.3627   248.7  690.23   255.9   693.5
   258.3  694.15     280  694.22   284.8  694.85   298.7  697.97   325.1  699.19
   336.4  700.46   340.2  702.22   347.7  708.12   359.1  712.15   373.3  721.28
   379.9  726.44   389.2  735.39   395.5  739.73   411.9  746.49     425  749.22
#Mann= 5, -1 ,  0
       0    0.07       0      80    0.06       0  197.27   0.045       0
  235.65    0.06       0   272.5     0.1       0
Bank Sta=197.27,235.65
XS Rating Curve= 0 ,0
Exp/Cntr(USF)=0,0
Exp/Cntr=0.3,0.1

Type RM Length L Ch R = 1 ,1639    ,143.5,142.4,140.3
XS GIS Cut Line= 2
1620689.23095828533002.6312157471620310.11664667533237.536973415
#Sta/Elev= 30
       0  697.44      51  697.06    81.8  697.91    95.3  696.92   123.9  696.84
   162.9  695.56     186  695.44   197.6  696.09   202.5  694.89  210.13688.8588
   214.4   687.8   236.2  687.15   245.4  687.45  257.57688.8609   274.8  692.47
   293.1  692.69   312.1  695.15   336.6  695.86   344.3   696.9   347.9   698.4
     355  702.78   359.7  705.11   366.1  707.74   382.9  713.16     391  717.88
   397.9  721.37   413.8  728.19   425.3  733.66   433.7  736.79     446  742.11
#Mann= 4, -1 ,  0
       0    0.07       0     140    0.06       0  210.13   0.045       0
  257.57     0.1       0
Bank Sta=210.13,257.57
XS Rating Curve= 0 ,0
Exp/Cntr(USF)=0,0
Exp/Cntr=0.3,0.1

Type RM Length L Ch R = 1 ,1497    ,196.6,195.4,194
XS GIS Cut Line= 6
1620564.97724201532880.1294191781620499.84384209532939.227726176
1620441.50143909532986.5826183411620360.12824225533044.706845924
1620299.02042484533088.1910109221620227.11243217533138.060661837
#Sta/Elev= 30
       0  694.73    15.2  694.74      59  695.75    68.9  695.23    91.6  695.31
   124.9  694.61   157.6  695.15   161.8  694.54   168.6  690.35  174.22688.0447
     178  687.19     182  687.04   218.3  686.81   222.3  687.35  223.77688.0463
   228.9  691.18   232.1  692.17   250.6  691.83   272.1  693.45   295.7  694.54
   316.8  697.33   321.5  698.43   343.1  705.63   367.1   712.6   383.1  715.83
   394.6  718.74   401.7  720.91   413.4  725.49     419  726.61   425.6  727.01
#Mann= 5, -1 ,  0
       0    0.07       0  117.95    0.06       0  157.95     0.1       0
  174.22   0.045       0  223.77     0.1       0
Bank Sta=174.22,223.77
XS Rating Curve= 0 ,0
Exp/Cntr(USF)=0,0
Exp/Cntr=0.3,0.1

Type RM Length L Ch R = 1 ,1302    ,201.7,205.8,209.3
XS GIS Cut Line= 2
1620564.29733017 532631.661710121620076.29449262533030.692823156
#Sta/Elev= 30
       0  724.47    14.8  717.54    25.9   710.2    38.7  700.43    42.9   698.7
    47.1  698.05    60.5  697.28    72.6  695.57   100.2  694.27   174.8   694.8
   242.4  693.62   301.4  694.23     310  693.46  320.72687.1667     324  685.85
   326.8  685.45   354.3  685.57   356.7  685.72  361.14 687.166   367.2  689.04
   377.6  689.12   390.4   691.2   462.5  694.71   496.8  699.91   507.1  700.18
   522.7  702.46   543.4  709.72   594.5   724.8   613.1   733.7   630.4  740.78
#Mann= 6, -1 ,  0
       0     0.1       0      70    0.07       0     310    0.06       0
  320.72   0.045       0  361.14    0.06       0     420     0.1       0
Bank Sta=320.72,361.14
XS Rating Curve= 0 ,0
Exp/Cntr(USF)=0,0
Exp/Cntr=0.3,0.1

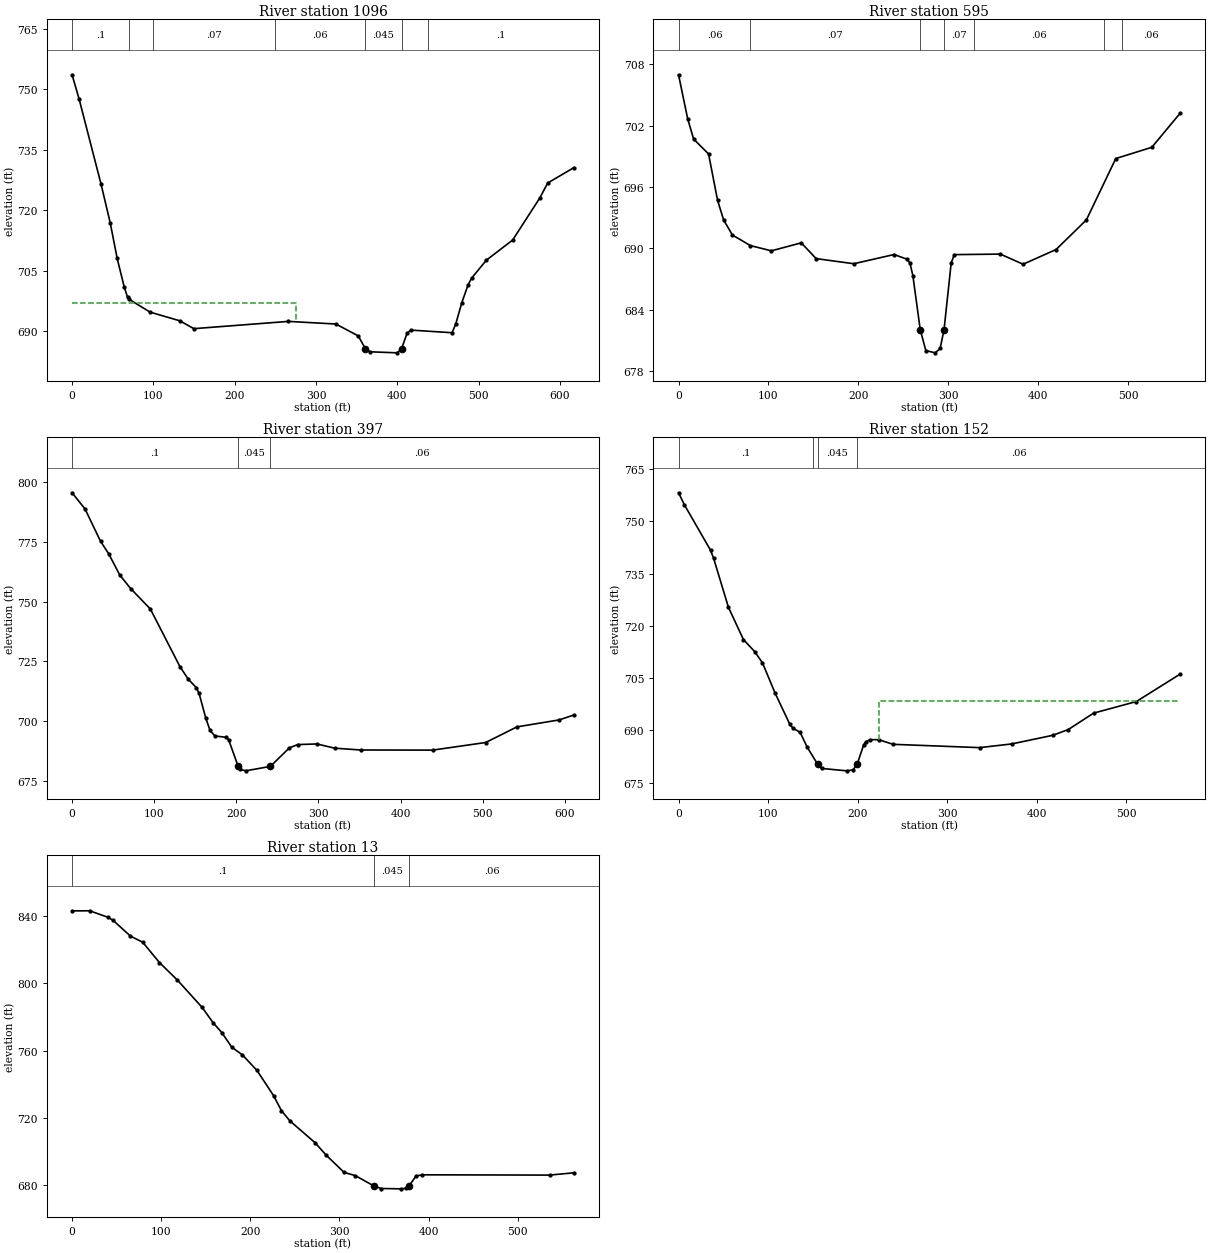
Type RM Length L Ch R = 1 ,1096    ,470.4,500.5,498
XS GIS Cut Line= 3
1620468.68158748532462.8917371611620247.79622973532647.689714174
1619962.08304457532811.161139543
#Sta/Elev= 30
       0  753.58     8.5  747.68    35.6  726.49      47  716.76    55.5  708.01
    64.1  700.96    68.3  698.34    70.5  697.83    96.1  694.68   132.5  692.54
   149.8  690.59   266.1  692.39   324.5  691.74     352  688.79  360.71685.6564
   366.4  684.85   400.1  684.59  405.36685.6551   412.1  689.49   416.9  690.23
   467.4  689.58   471.9  691.74   479.4  697.05     487  701.41   491.4  703.12
   509.7   707.6   541.9  712.57   575.6  723.11     585  726.72   617.2  730.54
#Mann= 7, -1 ,  0
       0     0.1       0      70    0.06       0     100    0.07       0
     250    0.06       0  360.71   0.045       0  405.36    0.06       0
  437.99     0.1       0
#XS Ineff= 2 , 0
          275.45  696.87
Permanent Ineff=
       F       F
Bank Sta=360.71,405.36
XS Rating Curve= 0 ,0
Exp/Cntr(USF)=0,0
Exp/Cntr=0.3,0.1

Type RM Length L Ch R = 1 ,595     ,197.4,198.4,174.4
XS GIS Cut Line= 4
1620314.76124649 532358.553696811620138.08516026532329.708239541
1619948.18051832532254.386227034 1619790.5606671532330.115436986
#Sta/Elev= 30
       0  706.96    10.2  702.65    16.8  700.68    33.4  699.23    43.4  694.71
    50.1  692.79      60  691.31      80  690.28   103.3  689.77   136.5  690.55
   153.1  689.01     195  688.51   239.8  689.41   253.9  688.96   257.4  688.59
   260.7  687.34  268.86682.0778   275.1  680.03   285.6  679.81     291  680.24
  295.38682.0795   303.3  688.59   306.8   689.4     358  689.45   383.3  688.46
     420   689.9   453.7  692.79   486.4  698.78   526.5  699.88   558.2  703.23
#Mann= 7, -1 ,  0
       0    0.06       0      80    0.07       0  268.86   0.045       0
  295.38    0.07       0  329.02    0.06       0  473.31    0.07       0
  493.31    0.06       0
Bank Sta=268.86,295.38
XS Rating Curve= 0 ,0
Exp/Cntr(USF)=0,0
Exp/Cntr=0.3,0.1

Type RM Length L Ch R = 1 ,397     ,243.7,245.3,228.1
XS GIS Cut Line= 3
1620329.02321057532086.087634381 1620035.6268596  532138.8789937
1619765.93159249532297.565052602
#Sta/Elev= 30
       0  795.37    15.7  788.66    34.7  775.12    44.7  769.85      58   761.1
    71.4  755.37    95.3  746.89   131.4  722.79   141.4  717.62   151.4  714.03
   154.7  711.62   162.6  701.59     168  696.19   173.9   693.9     188  693.31
   190.8  692.17  202.25681.1877   204.7  679.99   211.4  679.34  241.43 681.188
   264.7  688.95   274.7   690.3   298.1  690.56   319.8   688.8   351.3  688.04
   438.9  687.98   503.6  691.16   541.7  697.68     593  700.58     611  702.64
#Mann= 3, -1 ,  0
       0     0.1       0  202.25   0.045       0  241.43    0.06       0
Bank Sta=202.25,241.43
XS Rating Curve= 0 ,0
Exp/Cntr(USF)=0,0
Exp/Cntr=0.3,0.1

Type RM Length L Ch R = 1 ,152     ,139.8,138.7,138.6
XS GIS Cut Line= 2
1620094.62986395531857.4979979941619634.42553389532177.737507471
#Sta/Elev= 30
       0  758.19     6.6  754.72    35.8  741.69    39.2  739.39    55.8   725.3
    72.5  716.08    85.1  712.61    93.8  709.39   107.8  700.76   124.4  691.73
   127.8  690.63   135.8  689.48   143.8  685.17  155.51 680.256   159.8  679.09
     188   678.4   195.1  678.69  199.55680.2546   206.9  685.88   209.2  686.73
     214  687.34   223.7  687.34   239.7  686.01   336.5  685.06   372.3  686.12
   418.2   688.6   435.5  690.25   463.8  694.96   511.5  698.28   560.7  706.19
#Mann= 4, -1 ,  0
       0     0.1       0     150    0.06       0  155.51   0.045       0
  199.55    0.06       0
#XS Ineff= 2 , 0
                          223.86          698.45
Permanent Ineff=
       F       F
Bank Sta=155.51,199.55
XS Rating Curve= 0 ,0
Exp/Cntr(USF)=0,0
Exp/Cntr=0.3,0.1

Type RM Length L Ch R = 1 ,13      ,,,
XS GIS Cut Line= 4
1620147.62663354531642.793502591  1619928.052912531803.316499735
1619862.14112074531850.9513839311619692.01154304531973.499783798
#Sta/Elev= 30
       0  843.11    19.7  843.18    40.4  839.28    45.9  837.55    65.5  828.12
    79.3  824.45      98  812.42   118.2  801.96     146  785.69   158.2  776.65
   168.2  770.61   179.3     762   191.1  757.51   207.5  748.22   226.3  733.09
   234.9  724.34   244.3  718.31   272.8  705.19   284.9  697.97   305.2  687.64
   317.9  685.69     339  679.45   346.7  678.05   369.1  677.85   374.3  678.09
     378  679.55     386  685.53   393.1  686.19   535.7  686.02     563  687.39
#Mann= 3, -1 ,  0
       0     0.1       0     339   0.045       0     378    0.06       0
Bank Sta=339,378
XS Rating Curve= 0 ,0
Exp/Cntr(USF)=0,0
Exp/Cntr=0.3,0.1
LCMann Table=0

Chan Stop Cuts=-1
Use User Specified Reach Order=0
Composite Channel Slope=5